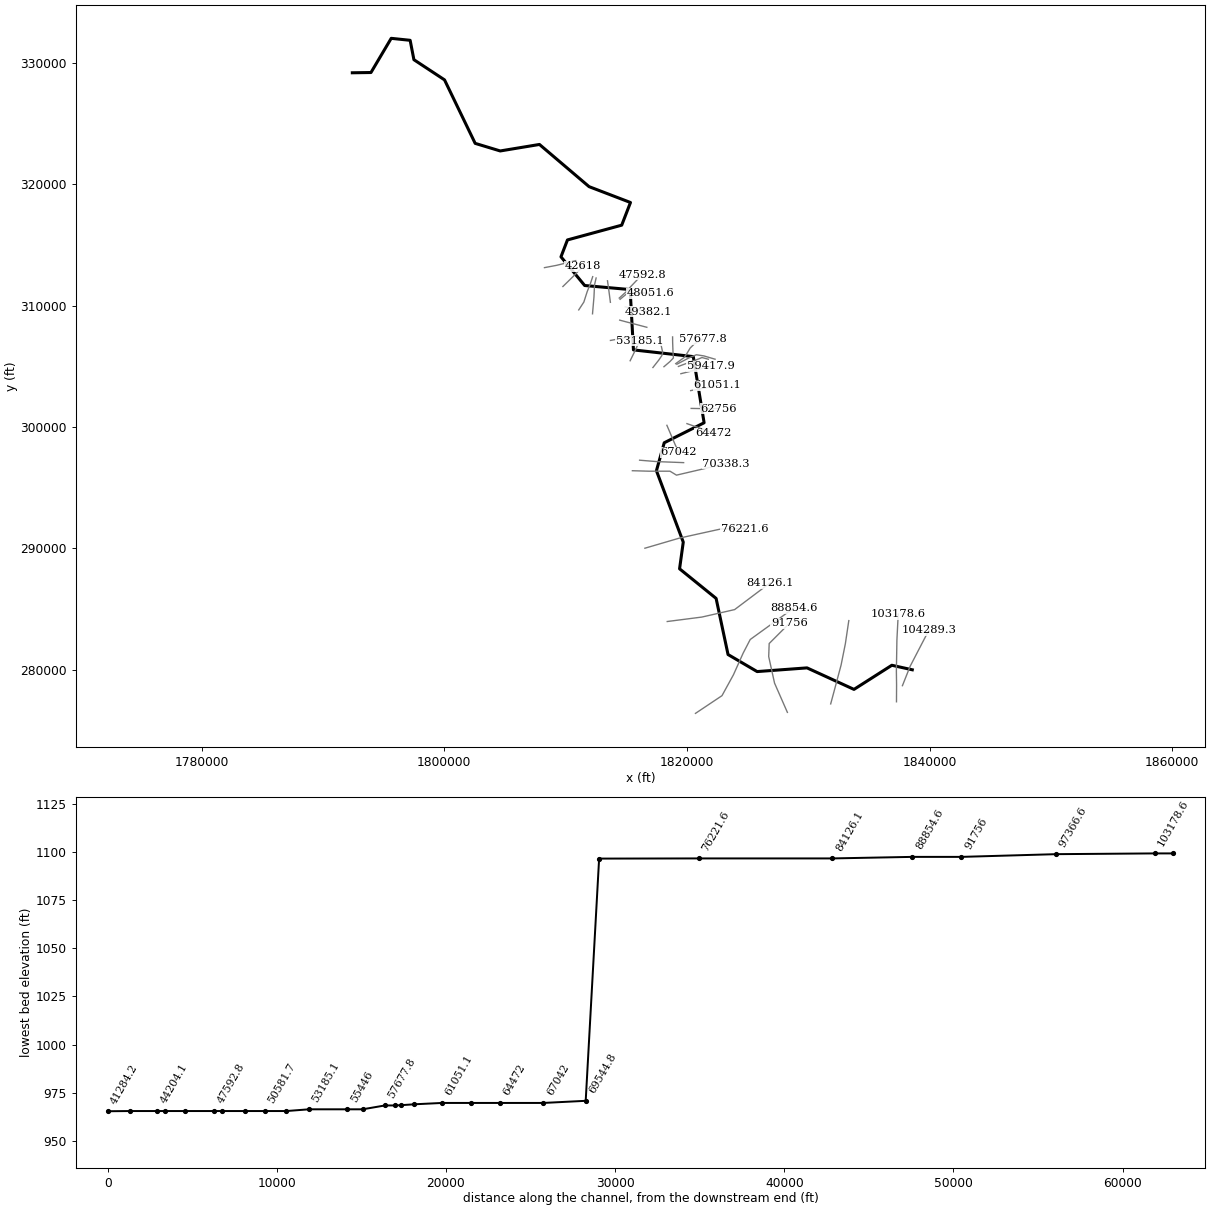
--- TygrtVyRvr.prj (project) ---

Proj Title=TygrtVyRvr
Current Plan=p01
Default Exp/Contr=0,0
English Units
Geom File=g01
Flow File=f01
Plan File=p01
BEGIN DESCRIPTION:
The Tygart Lake Dam, located on the Tygart Valley River, is a very large flood control facility constructed in the late 1930s. It was specifically designed to attenuate peak flows downstream.
A USGS gage (no. 03056000) is located just downstream of the dam:
http://waterdata.usgs.gov/nwis/nwisman/?site_no=03056000
The maximum recorded flow at the gage is 21100 cfs (1965). At this same location, the regression equations return a 100-yr flow of 85281 cfs (DA = 1182 mi^2, as listed on the USGS gage website). The difference is 64181 cfs.
Central Mountains Region
PK100(1%AOP) = 297 * DRNAREA ^ 0.800
To represent attenuated flows, a total of 64181 cfs was subtracted from each drainage point downstream of the dam.
The 100-year pool elevation is 1166.2' NGVD29 (subtracted 0.56' for NAVD88).
END DESCRIPTION:
DSS Export Rating Curves= 0
DSS Export Rating Curve Sorted= 0
DSS Export Volume Flow Curves= 0
DXF OffsetX= 0
DXF OffsetY= 0
DXF ScaleX= 0
DXF ScaleY= 0

--- TygrtVyRvr.p01 (plan) ---

Plan Title=Floodplain
Program Version=4.00
Geom File=g01
Flow File=f01
K Sum by GR=0
Std Step Tol=0.01
Critical Tol=0.01
Num of Std Step Trials=20
Max Error Tol=0.3
Flow Tol Ratio=0.001
Split Flow NTrial=30
Split Flow Tol=0.02
Split Flow Ratio=0.02
Log Output Level=0
Friction Slope Method=1
Unsteady Friction Slope Method=2
Unsteady Bridges Friction Slope Method=1
Global Log Level=0
CheckData=False
Run HTab=0
Run UNet=0
Run PostProcess=0
UNET Theta=0
UNET Theta Warmup=0
UNET ZTol=0
UNET ZSATol=0
UNET MxIter=0
UNET MaxInSteps=0
UNET DtIC=0
UNET DtMin=0
UNET MaxCRTS=0
UNET WFStab=0
UNET SFStab=0
UNET WFX=0
UNET SFX=0
UNET DSS MLevel=0
UNET DZMax Abort=0
UNET Convert EG Bridges=0
UNET Use Existing IB Tables=0
UNET Froude Limit=0
UNET Froude Power=0
Write IC File=0
Echo Input=False
Echo Output=False
Write Detailed=0

--- TygrtVyRvr.f01 (steady flow) ---

Flow Title=NFF Regression Equation
Program Version=4.10
Number of Profiles= 1
Profile Names=P100yr
River Rch & RM=TygrtVyRvr,Main            ,104289.3
   78484
River Rch & RM=TygrtVyRvr,Main            ,88854.6
   84756
River Rch & RM=TygrtVyRvr,Main            ,70338.3
   85111
River Rch & RM=TygrtVyRvr,Main            ,69544.8
   21054
River Rch & RM=TygrtVyRvr,Main            ,64472
   21080
River Rch & RM=TygrtVyRvr,Main            ,57677.8
   26952
River Rch & RM=TygrtVyRvr,Main            ,55446
   27748
River Rch & RM=TygrtVyRvr,Main            ,42618
   28190
River Rch & RM=TygrtVyRvr,Main            ,31806
   29067
River Rch & RM=TygrtVyRvr,Main            ,9687.4
   29722
River Rch & RM=TygrtVyRvr,Main            ,571.6
   29913
River Rch & RM=TygrtVyRvr,Main            ,150.8
   30746
Boundary for River Rch & Prof#=TygrtVyRvr,Main            , 1
Up Type= 0
Dn Type= 1
Dn Known WS=893.37
DSS Import GetInterval= 0
DSS Import GetPeak= 0
DSS Import FillOption= 0

--- TygrtVyRvr.g01 (geometry) ---

Geom Title=USGS 10m DEM
Program Version=4.10

River Reach=TygrtVyRvr      ,Main
Reach XY= 30
     1838571.506       279985.79      1836884.54       280358.77
     1833765.897      278370.087     1829895.476      280142.863
     1825783.085        279838.5     1823385.957      281243.188
     1822401.718      285869.117     1819390.971      288309.839
     1819695.057      290508.444     1817483.849       296393.55
     1818127.142      298696.909     1821412.929      300345.732
     1820520.119      305799.126     1815589.303      306350.431
     1815315.967      311322.277     1811570.026      311658.152
     1809616.363      314022.343     1810150.373      315413.822
     1814622.735      316631.102     1815344.207      318499.198
      1811931.41      319806.504     1807843.177      323283.658
     1804607.568       322748.14     1802544.201       323373.01
     1800018.458      328606.279     1797494.923      330269.386
      1797184.89       331867.65     1795624.499      332029.943
     1793955.987      329212.502     1792418.577      329190.869

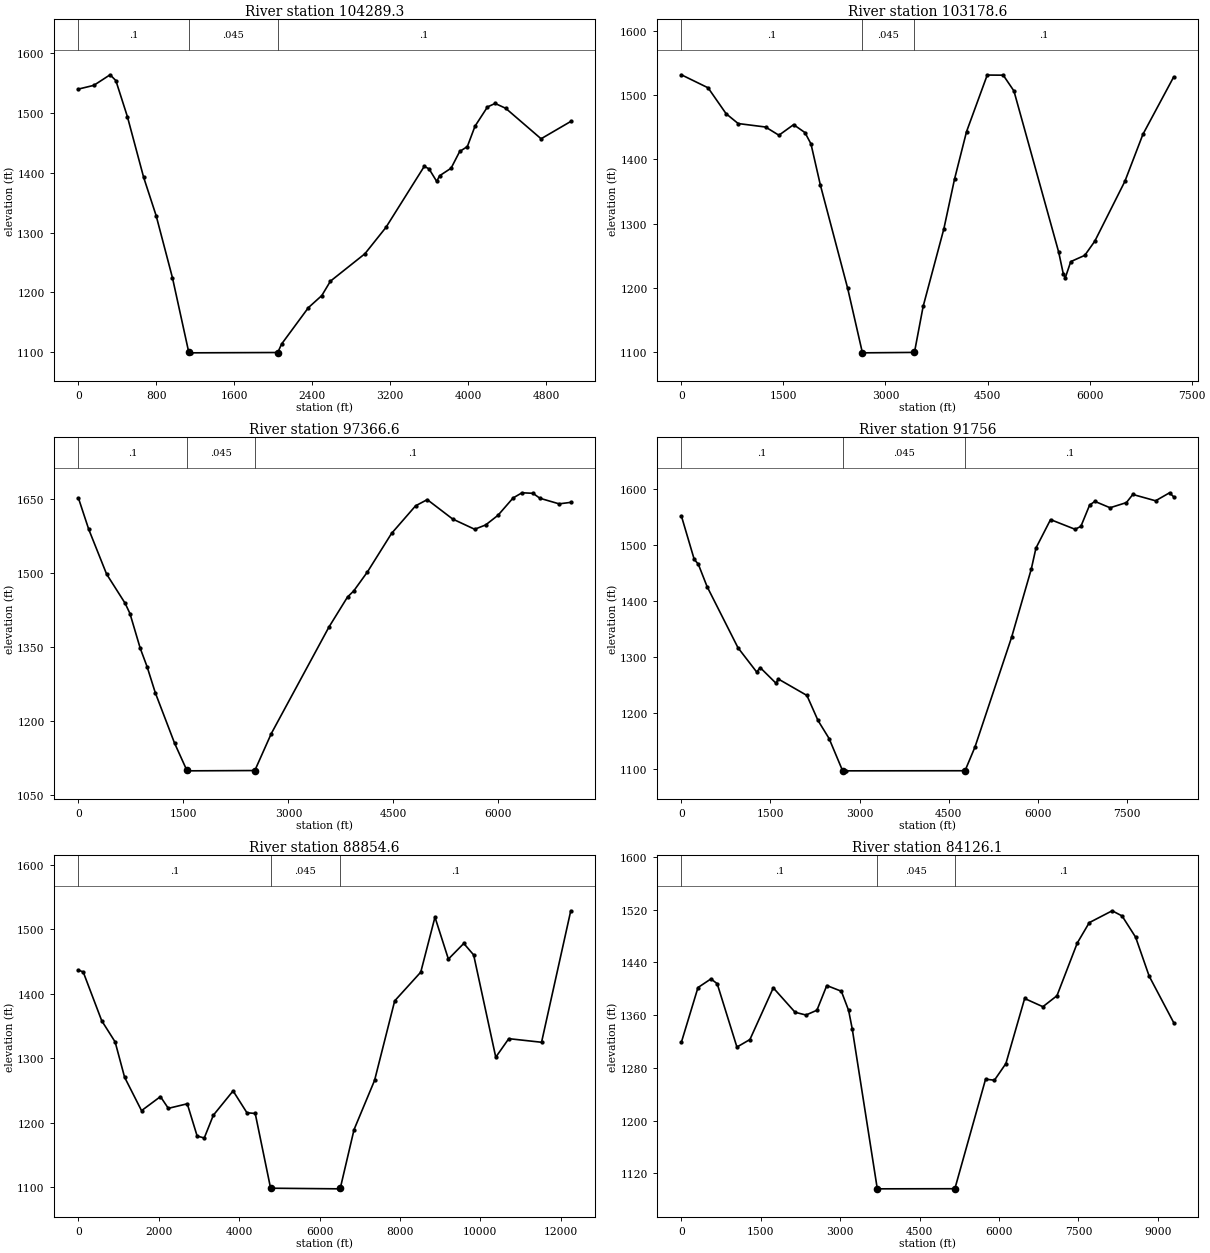
Type RM Length L Ch R = 1 ,104289.3,1102.3,1110.7,1119.1
XS GIS Cut Line= 4
     1837759.226      278676.665     1838274.045       279975.66
     1838403.224      280294.166     1839929.365      283233.956
#Sta/Elev= 30
       0 1539.42   157.4 1545.59   324.7 1563.25   383.8 1553.56   501.8  1493.6
   669.1 1392.05     797 1328.31   964.3 1224.79  1131.6 1100.58  1151.3  1099.2
  2045.7 1099.75    2085 1113.88  2360.2 1174.63  2497.8 1194.81  2586.3 1218.82
  2940.1 1264.53  3156.4 1308.61  3549.5 1410.41  3598.6 1406.21  3677.3 1385.27
  3706.8 1394.71  3824.7 1407.34  3913.2 1435.24  3991.8 1443.44  4070.4 1477.45
  4198.2 1509.54  4276.8 1515.42    4385 1507.37  4748.6 1456.45  5053.3 1485.36
#Mann= 3 , 0 , 0
       0      .1       0  1131.6    .045       0  2045.7      .1       0
Bank Sta=1131.6,2045.7
XS Rating Curve= 0 ,0
Exp/Cntr=0.3,0.1

Type RM Length L Ch R = 1 ,103178.6,5817.4,5811.9,5806.5
XS GIS Cut Line= 5
     1837268.648       277347.31     1837276.213      278741.888
     1837260.094      279870.241     1837303.497      282431.005
     1837412.004      284579.443
#Sta/Elev= 30
       0 1531.28   392.8 1511.02     658 1470.74   834.8 1455.51  1237.5  1450.1
  1433.8 1437.34  1649.7 1453.78  1816.6 1441.47  1904.9 1423.88  2042.2 1360.28
  2444.6 1199.31  2660.4 1099.56  2670.3  1099.2  3425.8 1099.88  3553.4 1171.29
  3857.6 1291.73  4014.6 1369.01  4191.2 1442.85  4495.4 1530.86  4730.9 1530.66
  4887.9 1506.14  5545.9 1255.61  5614.6 1221.38  5644.1 1216.19  5722.7 1240.93
    5929 1250.68  6076.3 1272.71  6518.3 1365.63  6783.5 1438.74  7235.4 1527.82
#Mann= 3 , 0 , 0
       0      .1       0  2660.4    .045       0  3425.8      .1       0
Bank Sta=2660.4,3425.8
XS Rating Curve= 0 ,0
Exp/Cntr=0.3,0.1

Type RM Length L Ch R = 1 ,97366.6 ,5599.8,5610.6,5621.4
XS GIS Cut Line= 5
     1831845.597      277174.061     1832106.014      278139.772
     1832702.802      280375.016     1833056.139      282137.326
     1833338.825      284039.124
#Sta/Elev= 30
       0 1651.27   147.1 1587.98     402  1497.4   666.8 1438.26   735.4 1417.59
   882.5 1347.13   980.6 1309.76  1098.2 1256.81  1372.7    1155  1549.2 1099.61
    1559 1098.81  2519.7 1099.43    2755 1174.31  3578.9  1390.2  3844.1 1451.03
  3932.5 1463.25    4129 1501.92  4472.7 1579.74  4816.5 1635.78  4983.4 1648.34
  5346.6 1609.02  5660.5  1588.3  5817.4 1596.98    5994 1616.58  6209.8  1651.7
  6337.3 1662.21  6494.3 1661.14  6592.4 1651.14  6867.1 1639.78  7033.8 1642.78
#Mann= 3 , 0 , 0
       0      .1       0  1549.2    .045       0  2519.7      .1       0
Bank Sta=1549.2,2519.7
XS Rating Curve= 0 ,0
Exp/Cntr=0.3,0.1

Type RM Length L Ch R = 1 ,91756   ,2915.8,2901.4,2886.9
XS GIS Cut Line= 5
     1828277.455      276474.733     1827218.427      278887.928
     1826736.657      281075.428     1826776.793      282151.086
     1828429.971      283804.749
#Sta/Elev= 30
       0 1551.51   216.3 1474.11   285.2 1465.52   432.7 1425.65   953.8 1316.59
  1268.5 1273.39  1327.5 1281.28    1593 1253.49  1632.3 1260.99  2114.2 1231.68
    2301 1187.08  2487.8 1154.94  2713.9  1097.9  2772.9  1097.4    4777 1097.59
  4943.8 1139.69  5560.3 1334.99    5893 1456.94  5971.3 1494.22  6216.9 1544.87
  6629.6 1527.65  6727.8 1532.79  6875.2 1570.81  6963.6 1577.31  7219.1 1565.96
  7494.2 1575.16  7602.2 1589.65  7985.4 1578.38  8221.2 1592.64    8290 1585.44
#Mann= 3 , 0 , 0
       0      .1       0  2713.9    .045       0    4777      .1       0
Bank Sta=2713.9,4777
XS Rating Curve= 0 ,0
Exp/Cntr=0.3,0.1

Type RM Length L Ch R = 1 ,88854.6 ,4749.7,4728.5,4707.4
XS GIS Cut Line= 6
     1820700.907      276393.352     1822887.653      277853.143
     1823833.011      279578.032      1824629.84      281356.833
     1825213.219      282481.678     1828812.132      285084.046
#Sta/Elev= 30
       0 1436.29   117.7 1433.54   578.8 1357.89   912.4 1325.08  1147.8  1270.4
  1569.7 1218.56  2040.6 1240.32  2236.8 1222.12  2707.9 1229.21  2953.8 1179.26
  3130.8 1176.18    3357 1211.47  3848.8 1249.16    4193 1215.31  4399.5 1214.21
  4782.3 1098.37  6496.3  1097.4  6515.9 1098.06  6859.6  1189.2  7370.4 1265.49
  7871.4 1388.71  8519.9 1433.21  8873.6 1518.43  9207.7 1453.45  9590.9  1477.7
  9836.5  1459.9 10386.8 1301.41   10711 1330.12 11526.6 1324.54 12253.7  1528.3
#Mann= 3 , 0 , 0
       0      .1       0  4782.3    .045       0  6515.9      .1       0
Bank Sta=4782.3,6515.9
XS Rating Curve= 0 ,0
Exp/Cntr=0.3,0.1

Type RM Length L Ch R = 1 ,84126.1 ,7904.5,7904.5,7904.5
XS GIS Cut Line= 4
     1818373.764      283964.255     1821224.504      284330.636
     1823928.497      284946.956     1826845.986      287141.338
#Sta/Elev= 30
       0 1318.76   313.9  1401.8   559.1 1414.93   676.9 1407.63  1049.6 1311.56
  1294.9    1323  1736.3 1401.36  2148.3 1364.31  2354.3 1360.14  2560.3 1367.43
  2746.7 1404.88  3021.7 1396.22  3159.4 1367.07  3228.2 1338.79  3700.3 1096.84
  3710.1  1096.6  5165.6 1096.78  5745.9 1262.89  5913.2 1261.32  6129.7 1286.56
  6483.9 1385.21  6828.3 1372.76    7094 1389.39  7477.8 1469.35  7704.1 1500.22
    8137 1518.22    8324 1510.36  8579.8 1478.18  8835.7 1419.12  9298.2 1348.72
#Mann= 3 , 0 , 0
       0      .1       0  3700.3    .045       0  5165.6      .1       0
Bank Sta=3700.3,5165.6
XS Rating Curve= 0 ,0
Exp/Cntr=0.3,0.1

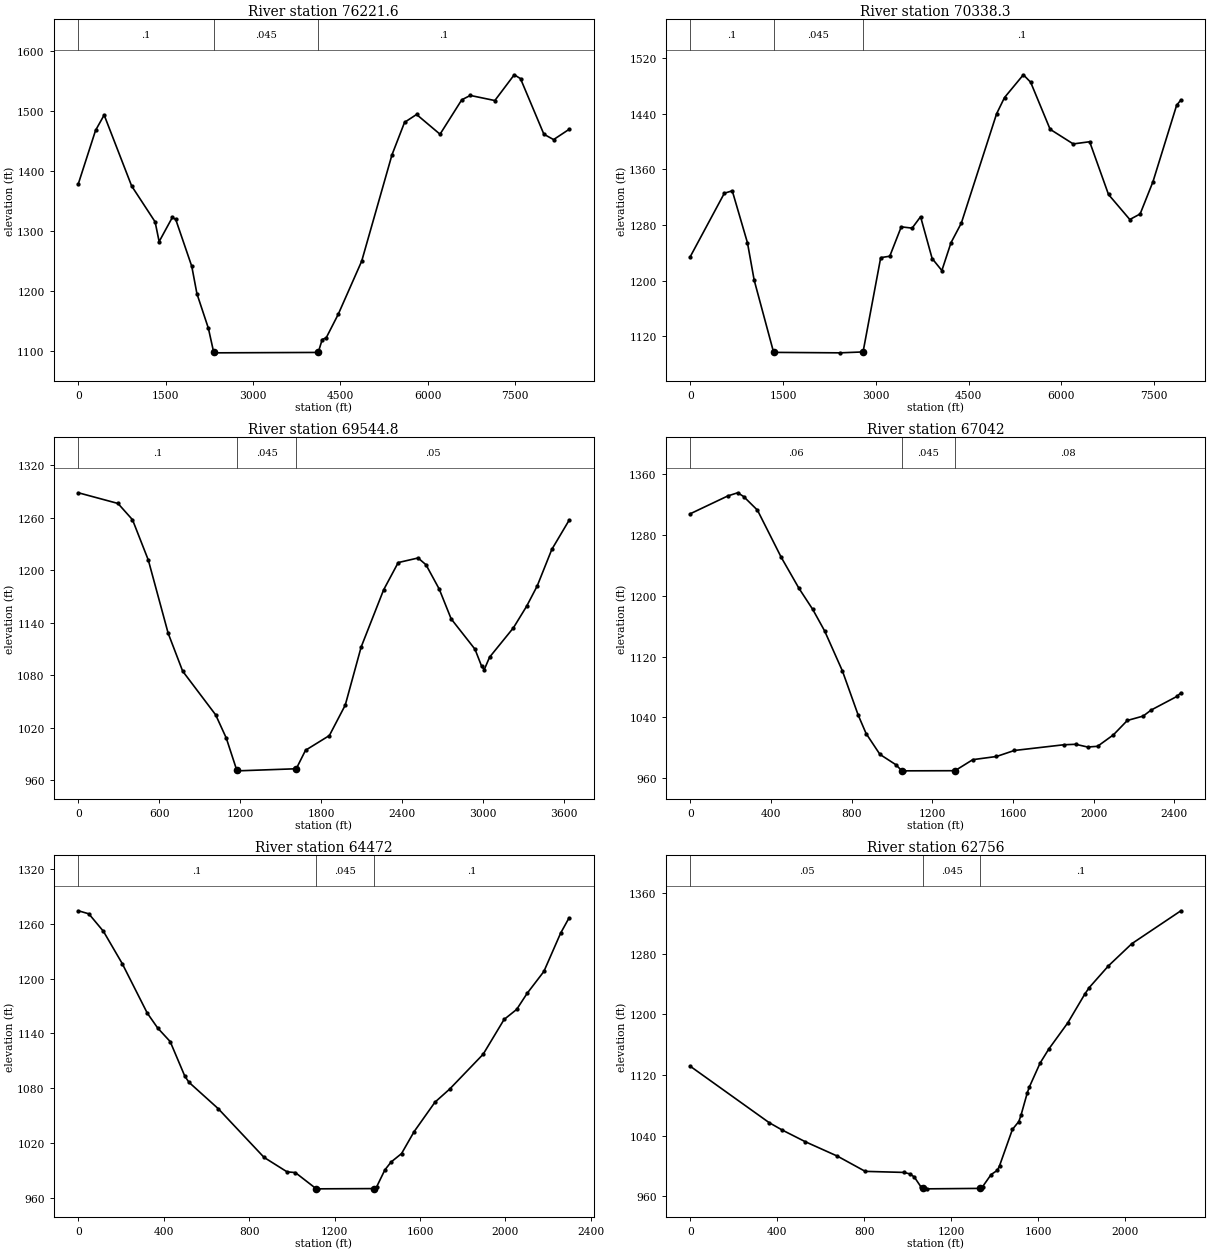
Type RM Length L Ch R = 1 ,76221.6 ,5888.3,5883.3,5878.3
XS GIS Cut Line= 5
     1816533.486      290005.921     1819356.448      290832.915
     1820957.226      291188.017     1822780.927      291588.123
     1824760.094      291627.186
#Sta/Elev= 30
       0 1378.49   295.1 1467.24   442.7 1492.83     915 1374.59  1318.3 1314.77
  1387.2  1281.9  1613.4 1322.15  1672.5 1318.79    1948 1240.66  2036.5 1195.08
  2233.3 1137.47  2321.8 1098.64  2341.5  1096.6  4119.8 1097.27  4188.6 1118.79
  4257.3 1121.65  4463.5 1160.79  4866.3 1249.25  5387.1 1426.52  5603.3 1480.64
  5809.6 1493.75  6212.5 1460.83  6585.6 1518.16  6732.6 1525.45    7154 1516.94
  7487.2 1559.87  7594.9 1553.46  7996.7 1460.82  8163.3 1451.89  8427.9 1468.86
#Mann= 3 , 0 , 0
       0      .1       0  2321.8    .045       0  4119.8      .1       0
Bank Sta=2321.8,4119.8
XS Rating Curve= 0 ,0
Exp/Cntr=0.3,0.1

Type RM Length L Ch R = 1 ,70338.3 ,795.3,793.5,792.5
XS GIS Cut Line= 5
     1815502.282      296392.811     1816869.469      296353.748
      1818601.24      296353.748     1819135.094      296028.227
     1823234.875      296985.088
#Sta/Elev= 30
       0 1234.69     551 1325.76     679 1329.24     925 1254.55  1033.2 1201.04
  1348.1 1097.18  2420.6 1096.51  2794.5 1097.81  3079.8 1233.21  3226.5 1235.31
  3412.2 1277.48    3588 1275.64  3724.8 1292.04  3911.7 1231.99  4069.1 1214.72
  4216.6 1254.67  4383.8 1282.85  4954.3 1439.92  5082.2 1463.19  5387.1  1495.9
  5505.2 1485.17  5819.9 1417.61  6193.7 1396.58  6459.3 1399.72  6764.2 1323.96
  7108.5 1288.01  7275.7    1296  7482.3 1342.07  7865.9 1452.09  7934.8 1459.72
#Mann= 3 , 0 , 0
       0      .1       0  1348.1    .045       0  2794.5      .1       0
Bank Sta=1348.1,2794.5
XS Rating Curve= 1 ,0
   85111 1165.64
Exp/Cntr=0.3,0.1

Type RM Length L Ch R = 1 ,69544.8 ,2527.2,2502.8,2477.5
XS GIS Cut Line= 3
      1816096.14      297260.432     1817490.237      297145.849
      1819725.48      297059.043
#Sta/Elev= 30
       0 1288.47   293.4 1276.27     401 1257.69   518.4 1211.54   665.2 1128.09
   772.8 1084.74  1017.3 1034.85  1095.6 1008.46  1173.8   971.6  1183.6   970.9
  1614.6  973.28  1683.3  994.41  1859.9  1011.2  1977.6 1045.96  2095.4 1112.29
  2262.2 1177.68  2370.1 1208.76  2517.3 1214.01  2576.1 1206.25  2674.2 1178.44
  2762.5 1144.45  2939.1 1109.79  2988.2 1090.38  3007.8 1086.52  3047.1 1100.69
  3223.7 1134.22  3321.8 1158.89  3400.3  1182.1  3508.2 1223.76  3635.7 1256.89
#Mann= 3 , 0 , 0
       0      .1       0  1173.8    .045       0  1614.6     .05       0
Bank Sta=1173.8,1614.6
XS Rating Curve= 0 ,0
Exp/Cntr=0.3,0.1

Type RM Length L Ch R = 1 ,67042   ,2551.8,2570.1,2588.3
XS GIS Cut Line= 3
      1818346.14      300135.432     1819019.403      298559.338
     1819318.362      297906.266
#Sta/Elev= 30
       0 1307.64   186.1 1331.06     235 1335.21   264.4  1330.3     333 1312.38
   450.5 1250.58   538.6 1209.73   607.2  1181.9     666 1153.66   754.1 1101.14
   832.4 1043.06   871.6 1018.84   940.2  991.42  1018.5  977.97  1047.9  970.11
  1057.7   969.8  1312.3  969.98  1400.5  984.49    1518  988.66  1606.1  996.53
  1851.6 1004.06  1910.6  1004.7  1969.7  1001.1  2018.9 1002.03  2097.6  1017.1
  2166.5 1035.99  2245.2 1041.78  2284.5 1049.66  2412.4 1067.59  2432.1 1072.36
#Mann= 3 , 0 , 0
       0     .06       0  1047.9    .045       0  1312.3     .08       0
Bank Sta=1047.9,1312.3
XS Rating Curve= 0 ,0
Exp/Cntr=0.3,0.1

Type RM Length L Ch R = 1 ,64472   ,1707.9,1716,1724.1
XS GIS Cut Line= 4
     1819998.918      300274.321     1820922.529      299954.877
     1821443.362      299760.432      1822158.64      299489.599
#Sta/Elev= 30
       0 1274.31    48.9 1270.98   117.3 1251.82   205.2 1216.54   322.5 1162.32
   371.4 1145.94     430 1131.07   498.4 1093.28     518 1086.47   654.8 1057.66
   869.8 1004.23   977.3  988.43  1016.3   987.6  1113.8  969.93  1123.6   969.8
  1386.9  970.08  1396.7  971.79  1435.7  990.57    1465  999.22  1513.7  1008.4
  1572.5  1032.4  1670.5 1064.76  1739.2 1079.06    1896  1117.2  1994.1  1155.3
  2052.9 1166.27    2102 1183.87  2180.4 1207.83  2258.8 1249.75  2298.1 1266.42
#Mann= 3 , 0 , 0
       0      .1       0  1113.8    .045       0  1386.9      .1       0
Bank Sta=1113.8,1386.9
XS Rating Curve= 0 ,0
Exp/Cntr=0.3,0.1

Type RM Length L Ch R = 1 ,62756   ,1700.8,1704.9,1709.2
XS GIS Cut Line= 3
     1820346.929      301528.279     1821484.646       301509.26
     1822602.296      301513.419
#Sta/Elev= 30
       0 1131.52   362.9 1057.08   421.8 1047.51   529.7 1031.84   676.8  1012.9
   804.4  992.85   980.9  991.47  1010.4   989.5    1030  985.36  1059.4  972.86
  1069.2  970.45  1088.8   969.8    1334  970.39  1343.8  972.62    1383  988.64
  1412.4  994.35  1422.2 1000.58    1481 1048.23  1510.4  1058.6  1520.2 1066.67
  1549.6 1096.72  1559.4 1104.53  1608.5 1135.85  1647.7 1154.02  1735.9 1188.95
  1814.4 1227.03    1834 1235.28  1922.2 1263.92    2030 1293.27  2255.5 1336.66
#Mann= 3 , 0 , 0
       0     .05       0  1069.2    .045       0    1334      .1       0
Bank Sta=1069.2,1334
XS Rating Curve= 0 ,0
Exp/Cntr=0.3,0.1

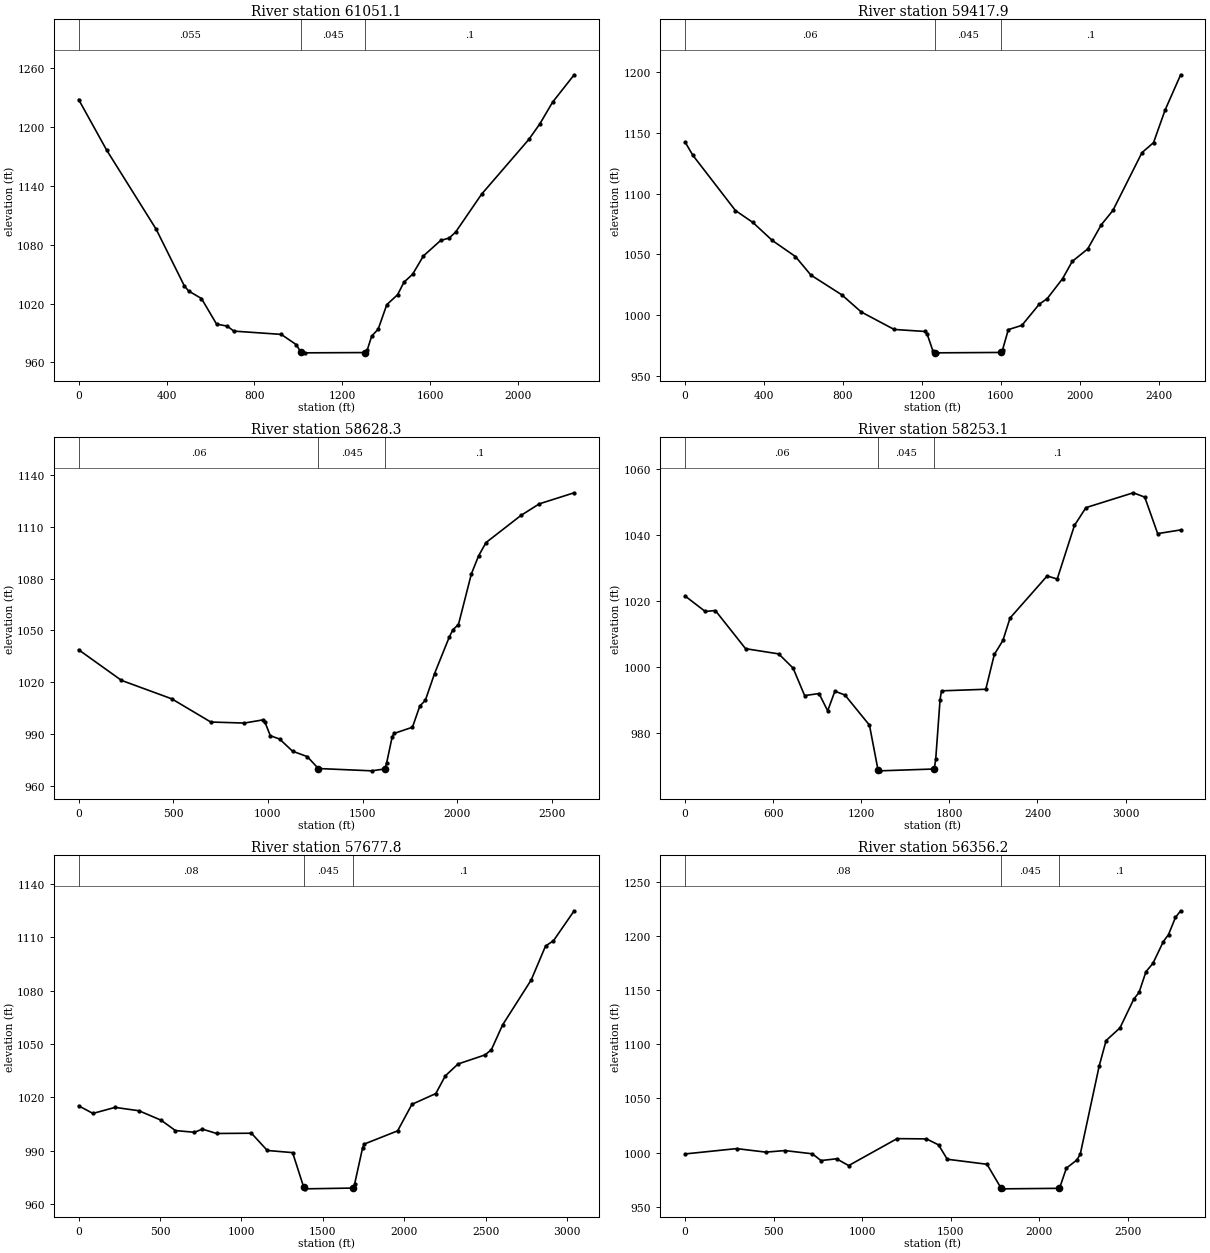
Type RM Length L Ch R = 1 ,61051.1 ,1632,1633.2,1634
XS GIS Cut Line= 3
     1820304.473      302996.543     1821424.206       303198.93
     1822519.751      303420.154
#Sta/Elev= 30
       0 1227.98   127.5 1176.43   353.1 1095.69   480.6 1038.29   500.3 1032.89
   559.1 1025.15   627.8   999.1   676.8     997   706.3  991.94   922.1  988.61
   990.7  978.13  1010.4  970.83    1030   969.8  1304.5  970.08  1314.4  973.18
    1334  986.94  1363.4  993.88  1402.6 1018.91  1451.6 1028.99    1481 1041.84
  1520.2 1049.91  1569.2 1068.52  1647.7 1084.32  1686.9 1086.81  1716.3 1092.98
    1834 1131.46  2049.6 1187.41  2098.7 1202.99  2157.5 1225.33  2255.5 1253.19
#Mann= 3 , 0 , 0
       0    .055       0  1010.4    .045       0  1304.5      .1       0
Bank Sta=1010.4,1304.5
XS Rating Curve= 0 ,0
Exp/Cntr=0.3,0.1

Type RM Length L Ch R = 1 ,59417.9 ,787,789.5,792
XS GIS Cut Line= 3
     1819498.764      304387.866     1820839.042      304728.143
     1821936.418      304989.599
#Sta/Elev= 30
       0 1142.42    39.2 1131.59     255 1086.15   343.2 1076.35   441.3 1061.58
     559 1048.31   637.5 1033.03   794.4 1016.76   892.4 1002.72  1059.2  988.34
  1216.1  986.67  1225.9  984.82  1255.3  970.82  1265.1  969.28  1274.9   969.1
  1598.6  969.42  1608.4  971.48  1637.8   988.2  1706.5   991.7  1794.8 1009.16
    1834 1013.54  1912.5 1030.05  1961.6 1044.28    2040 1054.54  2108.7 1074.41
  2167.6 1086.16  2314.7 1133.69  2373.6 1141.98  2432.4 1168.88  2510.9 1197.77
#Mann= 3 , 0 , 0
       0     .06       0  1265.1    .045       0  1598.6      .1       0
Bank Sta=1265.1,1598.6
XS Rating Curve= 0 ,0
Exp/Cntr=0.3,0.1

Type RM Length L Ch R = 1 ,58628.3 ,374,375.2,376.4
XS GIS Cut Line= 5
     1819296.372      304988.557     1820290.295      305361.821
     1820941.337      305596.196     1821236.476      305722.064
     1821761.649      305583.175
#Sta/Elev= 30
       0 1038.79   226.1 1021.05   491.5 1010.38     698  996.92   874.9  996.32
   973.2  998.15   983.1  997.12  1012.6  988.99  1061.7  987.06  1129.9  980.03
  1207.9  976.88  1266.4  969.98    1549  968.64  1617.2  969.73    1627  973.19
  1656.2  988.27  1665.9  990.29  1763.4  993.91  1802.3 1006.18  1831.4 1009.47
    1880 1024.93  1957.8 1046.11  1977.3 1050.42  2006.4 1053.37  2074.5 1082.68
  2113.3 1093.32  2152.1 1100.89  2336.4 1116.59  2433.4 1123.31  2617.7 1129.73
#Mann= 3 , 0 , 0
       0     .06       0  1266.4    .045       0  1617.2      .1       0
Bank Sta=1266.4,1617.2
XS Rating Curve= 0 ,0
Exp/Cntr=0.3,0.1

Type RM Length L Ch R = 1 ,58253.1 ,561,575.3,589.7
XS GIS Cut Line= 5
     1819169.925      305169.402     1820159.508      305690.235
     1820774.091      305950.652     1821388.675      305856.902
     1822317.263      305584.419
#Sta/Elev= 30
       0 1021.54   137.3 1016.85     206 1017.14     412 1005.56   637.6 1003.98
   735.7  999.66   814.2  991.33   912.3  991.95   971.1   986.7  1020.2  992.66
  1088.8   991.5  1255.7  982.36  1314.6  968.63  1324.4   968.5  1697.4  969.06
  1707.2  972.13  1736.7  990.14  1746.5  992.77    2048  993.25  2106.3 1003.82
  2164.6 1008.05  2213.2 1014.86  2466.1 1027.63  2534.5 1026.69  2651.8 1042.94
    2730 1048.35  3052.6 1052.86  3130.8 1051.54  3218.8 1040.47  3375.2 1041.59
#Mann= 3 , 0 , 0
       0     .06       0  1314.6    .045       0  1697.4      .1       0
#XS Ineff= 2 , 0
         1084.12  991.55
Permanent Ineff=
       F       F
Bank Sta=1314.6,1697.4
XS Rating Curve= 0 ,0
Exp/Cntr=0.3,0.1

Type RM Length L Ch R = 1 ,57677.8 ,1308.6,1321.5,1334.5
XS GIS Cut Line= 6
     1819072.703      305218.013     1819774.091       305728.43
     1820013.675      306082.597     1820263.675      306502.735
     1820603.953      306839.541      1821287.98      307218.013
#Sta/Elev= 30
       0  1015.2    87.7 1010.92   224.2 1014.31   370.4 1012.42   506.8  1007.1
   594.6 1001.27   711.5 1000.32   760.2 1002.08     848  999.64  1061.8  999.78
    1159  990.08  1314.6  988.87    1383  969.38  1392.8   968.5  1686.2  968.94
  1695.9  971.29  1744.8  991.65  1754.6  993.67  1959.8 1001.12  2047.8 1016.04
  2194.3 1022.08  2252.9 1032.06  2331.1 1038.72  2497.2 1043.84  2536.3 1046.83
  2604.7 1060.69  2780.6    1086  2868.6 1105.07  2917.4 1108.06  3044.5  1124.9
#Mann= 3 , 0 , 0
       0     .08       0    1383    .045       0  1686.2      .1       0
Bank Sta=1383,1686.2
XS Rating Curve= 0 ,0
Exp/Cntr=0.3,0.1

Type RM Length L Ch R = 1 ,56356.2 ,906.1,910.2,914.2
XS GIS Cut Line= 6
     1818103.953      304964.541     1818603.953      305395.097
      1818881.73      305683.291     1818847.008      306238.847
      1818819.23      306988.847     1818815.758      307419.402
#Sta/Elev= 30
       0  998.74   291.1 1003.67   456.1  1000.4   562.8 1001.86   718.4  998.87
   767.2  992.63   855.1  994.27   923.4  987.98  1196.8 1012.88  1362.8 1012.65
  1431.2  1007.1    1480  993.85  1704.5   989.2  1782.4  967.56  1792.2   966.5
  2113.8  966.97  2152.8  985.64  2211.3  993.07  2230.8  998.33    2338 1080.01
    2377 1103.52  2455.3 1115.19  2533.6 1141.89    2563 1147.93  2602.1 1167.14
  2641.3 1174.79    2700  1194.9  2729.3 1201.42  2768.5 1217.21  2797.8 1223.39
#Mann= 3 , 0 , 0
       0     .08       0  1782.4    .045       0  2113.8      .1       0
#XS Ineff= 2 , 0
         1565.98  990.69
Permanent Ineff=
       F       F
Bank Sta=1782.4,2113.8
XS Rating Curve= 0 ,0
Exp/Cntr=0.3,0.1

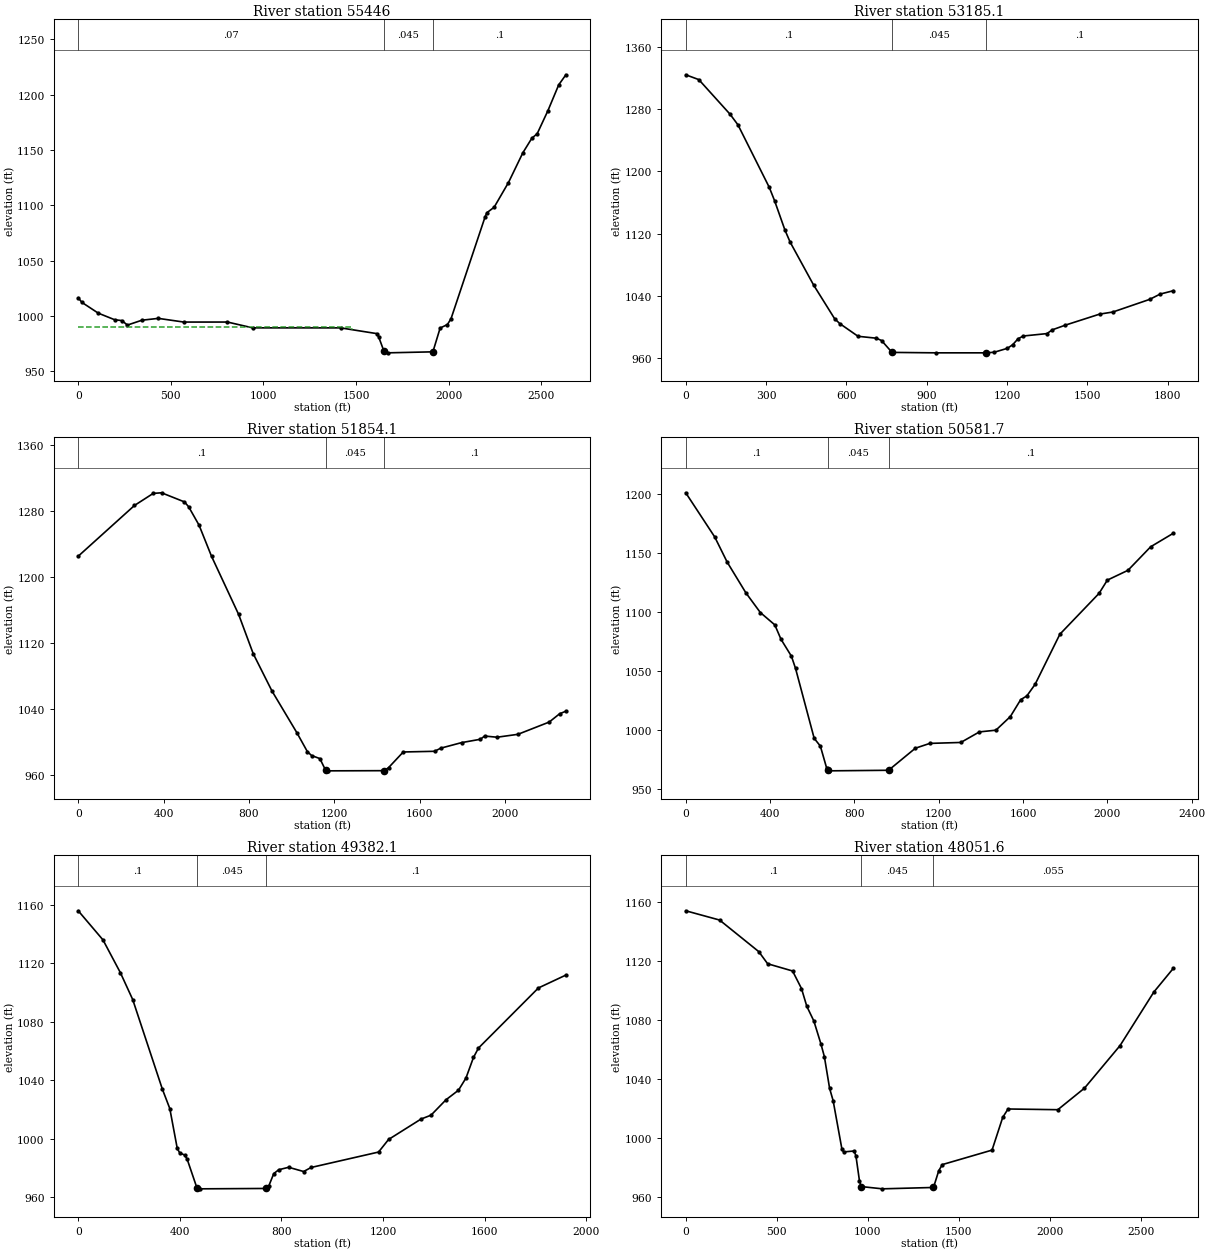
Type RM Length L Ch R = 1 ,55446   ,2276.1,2260.9,2245.7
XS GIS Cut Line= 6
     1817193.767        304898.8     1817686.823        305523.8
     1817929.878      305884.911     1817999.323        306148.8
     1817881.267      306683.522     1817735.434      307246.022
#Sta/Elev= 30
       0 1016.27    19.7 1012.14   108.1  1002.4   196.6  996.44   235.9  995.66
   265.4  991.61     344  996.02   432.4  997.67     570  994.34   805.7  994.35
   941.2  989.11  1416.5  989.08  1611.8   983.9  1621.6  981.15  1650.9  967.85
  1670.5   966.5  1914.9  967.41    1954  988.94  1993.2   992.1  2012.7  997.33
  2197.1  1089.7  2206.8 1093.28  2245.5 1098.18    2323 1120.55  2400.5 1147.42
  2448.9 1160.56    2478  1164.7  2536.1  1185.6  2594.2 1208.89  2632.9    1218
#Mann= 3 , 0 , 0
       0     .07       0  1650.9    .045       0  1914.9      .1       0
#XS Ineff= 2 , 0
         1476.03   990.2
Permanent Ineff=
       F       F
Bank Sta=1650.9,1914.9
XS Rating Curve= 0 ,0
Exp/Cntr=0.3,0.1

Type RM Length L Ch R = 1 ,53185.1 ,1353.4,1331,1308.6
XS GIS Cut Line= 3
     1815318.208       305457.31     1815738.779      306315.166
     1816097.391      307102.649
#Sta/Elev= 30
       0 1324.29    48.8 1318.08   165.7 1273.46     195 1259.86     312 1179.38
   331.5 1162.48   370.5  1124.4     390 1108.87   477.7  1053.6   555.7 1010.52
   575.2 1004.11   643.4  987.78   711.7  985.34   731.2  982.32   770.2  967.06
   935.9   966.5  1122.6   966.5  1152.1   967.3  1201.2  972.34  1220.9     977
  1240.6  984.53  1260.2  988.16  1348.7  991.26  1368.4  996.07  1417.6 1002.17
  1545.4 1016.32  1594.5 1019.01  1732.2 1035.28  1771.5 1042.13  1820.7 1046.43
#Mann= 3 , 0 , 0
       0      .1       0   770.2    .045       0  1122.6      .1       0
Bank Sta=770.2,1122.6
XS Rating Curve= 0 ,0
Exp/Cntr=0.3,0.1

Type RM Length L Ch R = 1 ,51854.1 ,1281.1,1272.5,1263.8
XS GIS Cut Line= 3
     1813693.208      307130.921     1814845.655      307340.496
     1815949.822      307486.329
#Sta/Elev= 30
       0 1225.38   263.6 1286.79   351.4 1301.38   390.4 1302.13   497.8 1291.08
   517.4 1285.18   566.2 1262.91   624.7 1225.21   751.6 1154.91   819.9 1107.42
   907.8 1062.24  1024.9 1011.58  1073.7  988.84  1093.3  984.16  1132.3  980.41
 1159.41   966.2  1171.4   965.6  1435.1  965.81  1454.7  969.62  1523.1  988.43
  1669.6  989.25  1698.9  993.04  1796.6  999.77  1884.5 1003.81  1904.1 1007.71
  1962.7 1006.29  2060.4  1009.8    2207 1024.64  2255.8 1034.68  2285.1 1037.78
#Mann= 3 , 0 , 0
       0      .1       0 1159.41    .045       0  1435.1      .1       0
Bank Sta=1159.41,1435.1
XS Rating Curve= 0 ,0
Exp/Cntr=0.3,0.1

Type RM Length L Ch R = 1 ,50581.7 ,1199.1,1199.5,1200
XS GIS Cut Line= 4
     1814457.097      308804.532     1815026.542      308651.755
     1815595.986      308505.921     1816693.208      308214.255
#Sta/Elev= 30
       0 1200.87   137.6 1163.47   196.5 1142.22     285 1116.29   353.8 1099.55
   422.5  1089.1     452 1076.86   501.2 1062.62   520.8 1052.26   609.2  993.11
   638.6  986.49     668  968.12  676.16  965.98   677.8   965.6   961.9  966.07
  1089.2  984.76  1157.8  988.82  1304.6  989.61  1392.7  998.54    1471    1000
  1539.5  1011.5  1588.5  1025.8  1617.8 1028.99    1657  1038.8  1774.4 1081.18
  1960.4 1115.78  1999.5 1126.96  2097.4 1135.27  2205.1 1155.19  2312.7 1166.65
#Mann= 3 , 0 , 0
       0      .1       0  676.16    .045       0   961.9      .1       0
Bank Sta=676.16,961.9
XS Rating Curve= 0 ,0
Exp/Cntr=0.3,0.1

Type RM Length L Ch R = 1 ,49382.1 ,1325,1330.5,1335.8
XS GIS Cut Line= 3
     1814913.364      309902.996     1815719.962      309714.734
     1816788.364      309491.538
#Sta/Elev= 30
       0    1156    97.4 1136.06   165.7 1113.68   214.4 1095.24   331.3  1033.8
   360.5 1020.55   389.8  993.28   399.5  990.24     419  988.72   428.8  985.92
   467.7  965.99   477.5   965.6   740.6  965.86   750.3  967.66   769.8  976.05
   789.3  978.68   828.3  980.36   887.3  977.46   916.8  980.23  1182.3  990.79
  1221.6  999.39  1349.4 1013.37  1388.8 1016.04  1447.8 1026.59  1496.9 1033.13
  1526.4 1041.48  1555.9 1055.56  1575.6    1062  1811.6 1103.16  1919.7 1111.97
#Mann= 3 , 0 , 0
       0      .1       0   467.7    .045       0   740.6      .1       0
Bank Sta=467.7,740.6
XS Rating Curve= 0 ,0
Exp/Cntr=0.3,0.1

Type RM Length L Ch R = 1 ,48051.6 ,439.8,458.8,477.8
XS GIS Cut Line= 5
     1814491.489      310522.788     1815001.905      310949.871
      1815205.03      311038.413     1815746.697      311064.454
     1816996.697      311027.996
#Sta/Elev= 30
       0 1153.84     186 1147.57   401.3  1126.2   450.2 1117.97   587.2 1113.08
   636.2 1101.19   665.5 1089.14   704.1 1079.24   742.6 1063.87   761.9 1055.13
   790.8 1033.53     810 1025.35   858.2  992.61   867.8  990.59   925.8  991.22
   935.5   987.8   954.9  970.92   964.6  967.14  1080.8   965.6  1361.6  966.53
  1390.7  977.91    1410  982.01  1683.4  991.82    1742 1013.95  1771.3 1019.66
  2044.9 1019.17  2191.4 1033.77  2386.8 1062.56  2572.5 1098.82  2679.9 1114.91
#Mann= 3 , 0 , 0
       0      .1       0   964.6    .045       0  1361.6    .055       0
Bank Sta=964.6,1361.6
XS Rating Curve= 0 ,0
Exp/Cntr=0.3,0.1

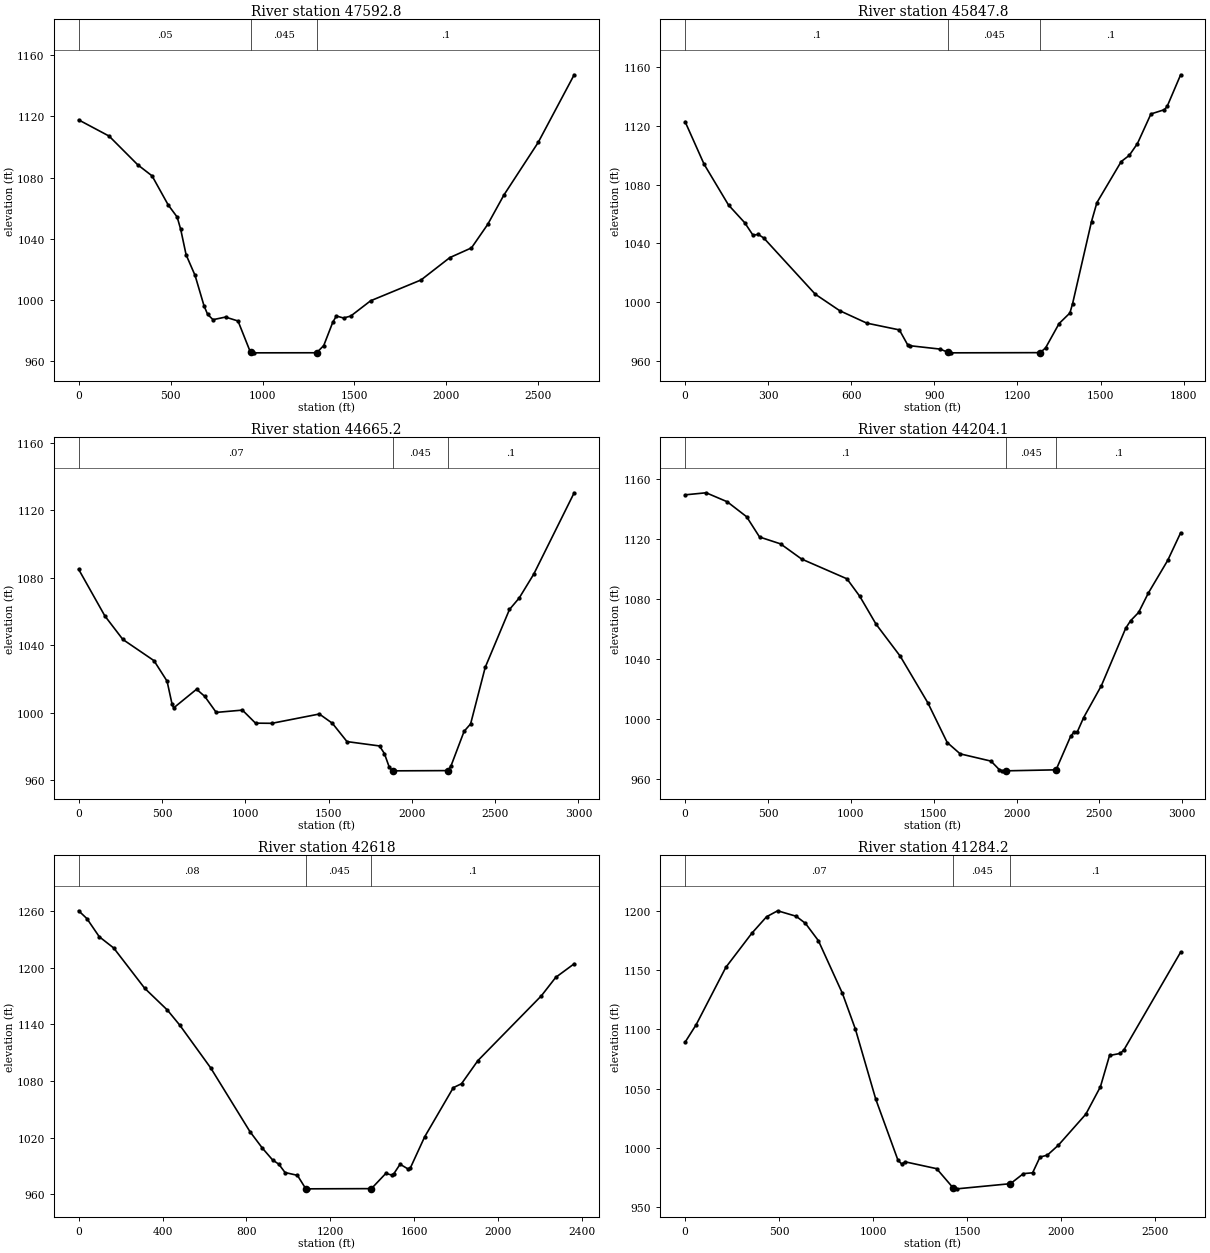
Type RM Length L Ch R = 1 ,47592.8 ,1725.5,1745,1764.5
XS GIS Cut Line= 4
     1814418.572      310621.746     1815001.905      311152.996
     1815366.489      311569.663      1816298.78      312548.829
#Sta/Elev= 30
       0 1117.62   165.6 1107.05   321.4 1088.31   399.4 1081.07     487 1062.12
   535.7 1054.22   555.2  1046.1   584.4 1029.58   633.1 1016.13   681.8  996.31
   701.3  990.75   730.6  987.24   798.7  988.94   866.7  986.38   934.7  965.85
   954.1   965.6  1294.1  965.65  1332.9  970.37  1381.8  985.51  1401.4  989.64
  1440.6  988.33  1479.8  989.61  1587.6  999.56  1861.9 1013.16  2018.6 1027.76
  2136.2 1034.09  2224.4 1049.41  2312.6  1068.6  2498.7 1102.86  2694.6 1147.05
#Mann= 3 , 0 , 0
       0     .05       0   934.7    .045       0  1294.1      .1       0
Bank Sta=934.7,1294.1
XS Rating Curve= 0 ,0
Exp/Cntr=0.3,0.1

Type RM Length L Ch R = 1 ,45847.8 ,1186.8,1182.6,1178.4
XS GIS Cut Line= 3
     1813689.405      310272.788      1813545.96      311370.031
     1813450.401      312045.808
#Sta/Elev= 30
       0 1122.72    68.6  1093.8   156.7 1066.08   215.4 1054.01   244.8 1045.64
   264.4 1046.06     284 1043.66     470 1005.45   558.2  994.25   656.1  985.78
   773.6  981.19     803  971.24   812.8  970.42   920.5  968.15   949.9  965.91
   959.7   965.6  1282.1  965.73  1301.6  969.01  1350.3  985.52  1389.3  992.67
  1399.1  999.12  1467.3 1054.86  1486.8  1067.7  1574.6 1095.62  1603.8 1099.84
  1633.1 1107.83  1681.8 1127.95  1730.6 1130.88  1740.3 1133.05  1789.1 1154.59
#Mann= 3 , 0 , 0
       0      .1       0   949.9    .045       0  1282.1      .1       0
Bank Sta=949.9,1282.1
XS Rating Curve= 0 ,0
Exp/Cntr=0.3,0.1

Type RM Length L Ch R = 1 ,44665.2 ,468.6,461.1,453.4
XS GIS Cut Line= 4
     1812215.447      309324.871     1812335.239      310715.496
     1812382.114      311710.288     1812512.322      312277.996
#Sta/Elev= 30
       0 1084.97   157.3 1057.37   265.4 1043.42   452.2 1030.87   530.8 1018.72
   560.3 1005.31   570.1 1002.86   707.7 1013.92   756.9 1009.71   825.7 1000.21
   982.9 1001.57  1061.6  993.85  1159.9  993.75  1444.6  999.26  1522.7  993.79
  1610.6  982.92  1805.8  980.34  1835.1  975.84  1864.4  967.75    1884  965.61
  1893.7   965.6  2215.9  965.74  2235.4  968.65  2313.6  989.03  2352.6  993.42
  2440.2  1026.9  2585.8 1061.18  2644.1 1067.96  2731.4 1082.09  2974.1  1130.3
#Mann= 3 , 0 , 0
       0     .07       0    1884    .045       0  2215.9      .1       0
Bank Sta=1884,2215.9
XS Rating Curve= 0 ,0
Exp/Cntr=0.3,0.1

Type RM Length L Ch R = 1 ,44204.1 ,1594.8,1586.1,1577.4
XS GIS Cut Line= 5
      1811080.03      309647.788     1811501.905      310293.621
     1811777.947      311158.204     1812038.364      311804.038
     1812231.072      312387.371
#Sta/Elev= 30
       0 1149.69   126.9 1151.07   253.9 1145.09   371.1  1135.1   449.2 1121.57
   576.1 1116.98   703.1 1106.86   976.4 1093.69  1054.4 1081.92    1152 1063.43
  1298.4 1041.99  1464.3 1011.01  1581.4  984.49  1659.5  976.93  1845.7  972.08
  1894.8  966.49  1914.4   965.6    1934   965.6    2238  966.27  2326.3  988.71
  2345.9  991.35  2365.6  991.43  2404.6 1001.15  2511.9  1022.5  2658.2 1060.71
  2687.4 1065.69  2736.2 1071.25  2794.7 1084.17  2911.7 1105.98  2989.7 1124.36
#Mann= 3 , 0 , 0
       0      .1       0    1934    .045       0    2238      .1       0
Bank Sta=1934,2238
XS Rating Curve= 0 ,0
Exp/Cntr=0.3,0.1

Type RM Length L Ch R = 1 ,42618   ,1346.8,1333.8,1320.8
XS GIS Cut Line= 3
     1809775.271      311576.824     1810633.625      312415.901
     1811441.937      313250.435
#Sta/Elev= 30
       0 1260.58    39.4 1252.29    98.4 1233.03   167.3 1221.08   314.8 1178.39
   423.1 1155.25   482.1 1139.26   629.7 1093.83   816.6 1026.33   875.7 1008.84
   924.8  996.22   954.4  991.72   983.9  982.92  1042.9  979.92  1082.3  965.87
  1092.1   965.6  1395.6  965.82    1464  981.89  1493.2  980.25    1503  981.77
  1532.3   991.7  1571.3  986.54  1581.1  987.66  1649.4 1020.72  1786.1 1072.94
  1825.2 1077.11  1903.3 1101.66    2206 1170.43  2274.3 1189.94  2362.2 1204.34
#Mann= 3 , 0 , 0
       0     .08       0  1082.3    .045       0  1395.6      .1       0
Bank Sta=1082.3,1395.6
XS Rating Curve= 0 ,0
Exp/Cntr=0.3,0.1

Type RM Length L Ch R = 1 ,41284.2 ,1242.2,1232,1221.8
XS GIS Cut Line= 4
     1808255.708      313130.921      1809241.82      313318.421
     1810214.042      313554.532     1810825.153       313707.31
#Sta/Elev= 30
       0 1089.22      59 1104.04   216.5 1152.36   354.3 1181.07     433 1195.05
     492  1200.1   590.5 1195.47   639.7 1189.49   708.6 1174.87   836.5 1130.33
   905.4 1100.19  1013.6 1041.12  1131.3  989.77  1150.9  986.54  1170.5  988.26
  1337.3  982.51  1425.6  966.15  1445.2   965.5  1729.6  969.85  1798.3  978.33
  1847.3  979.02  1886.6  992.32  1925.8  993.93  1984.6 1002.38  2130.2 1028.49
  2207.8 1051.63  2256.2    1078  2314.4 1079.79  2333.8 1083.05  2634.2  1165.2
#Mann= 3 , 0 , 0
       0     .07       0  1425.6    .045       0  1729.6      .1       0
Bank Sta=1425.6,1729.6
XS Rating Curve= 0 ,0
Exp/Cntr=0.3,0.1