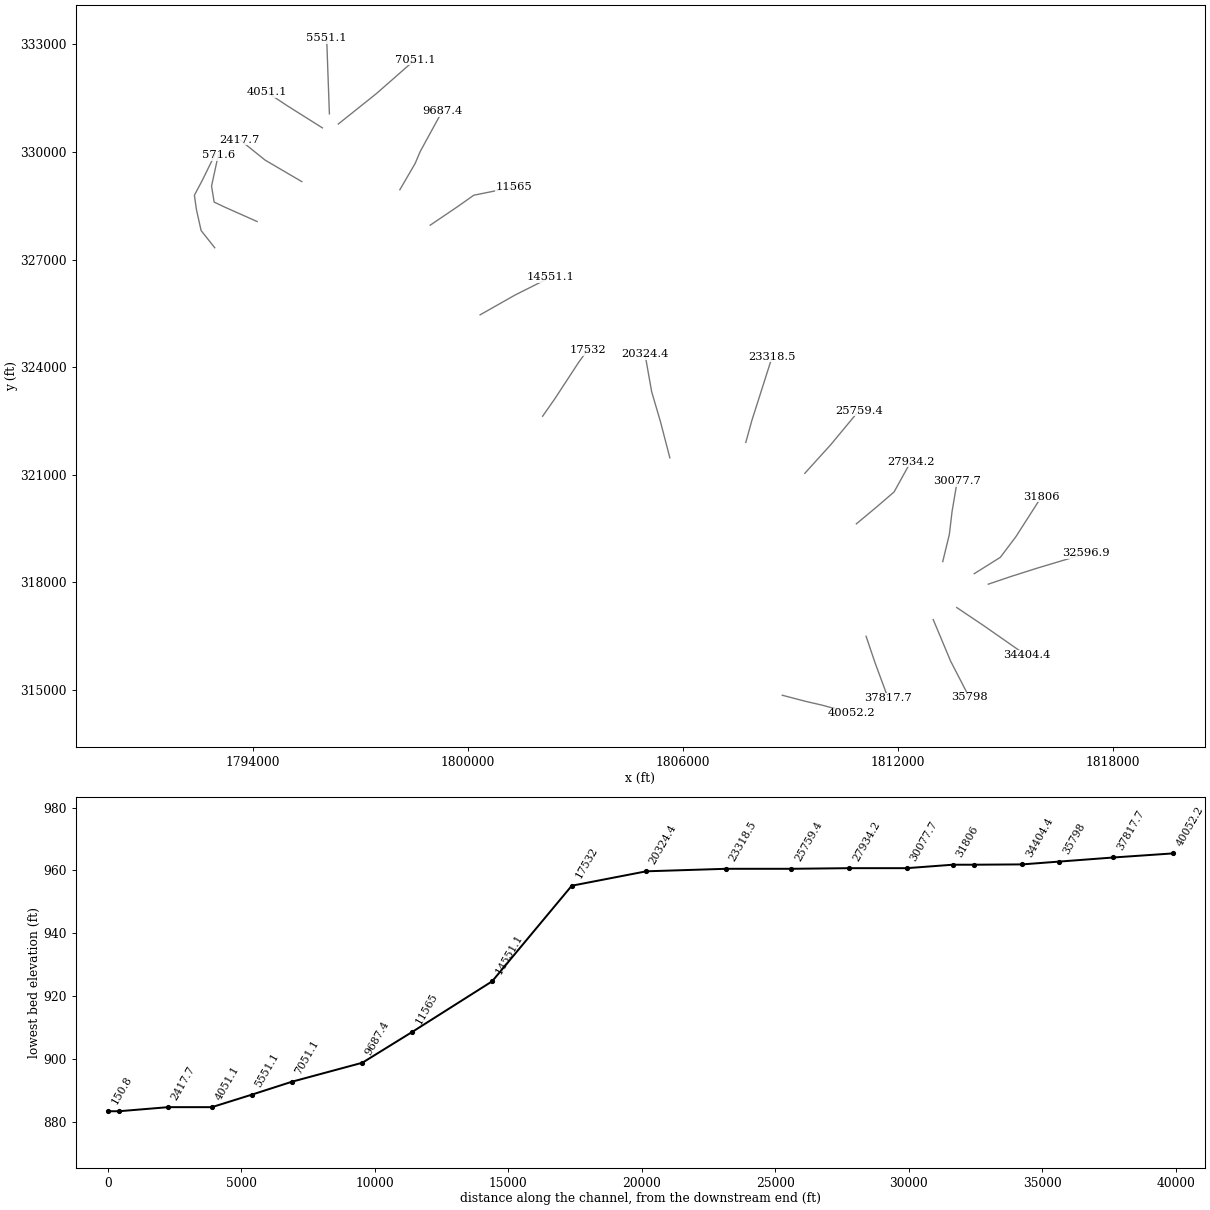
HEC-RAS study TygrtVyRvr.prj: TygrtVyRvr

--- TygrtVyRvr.g01 (geometry) --- (continued)

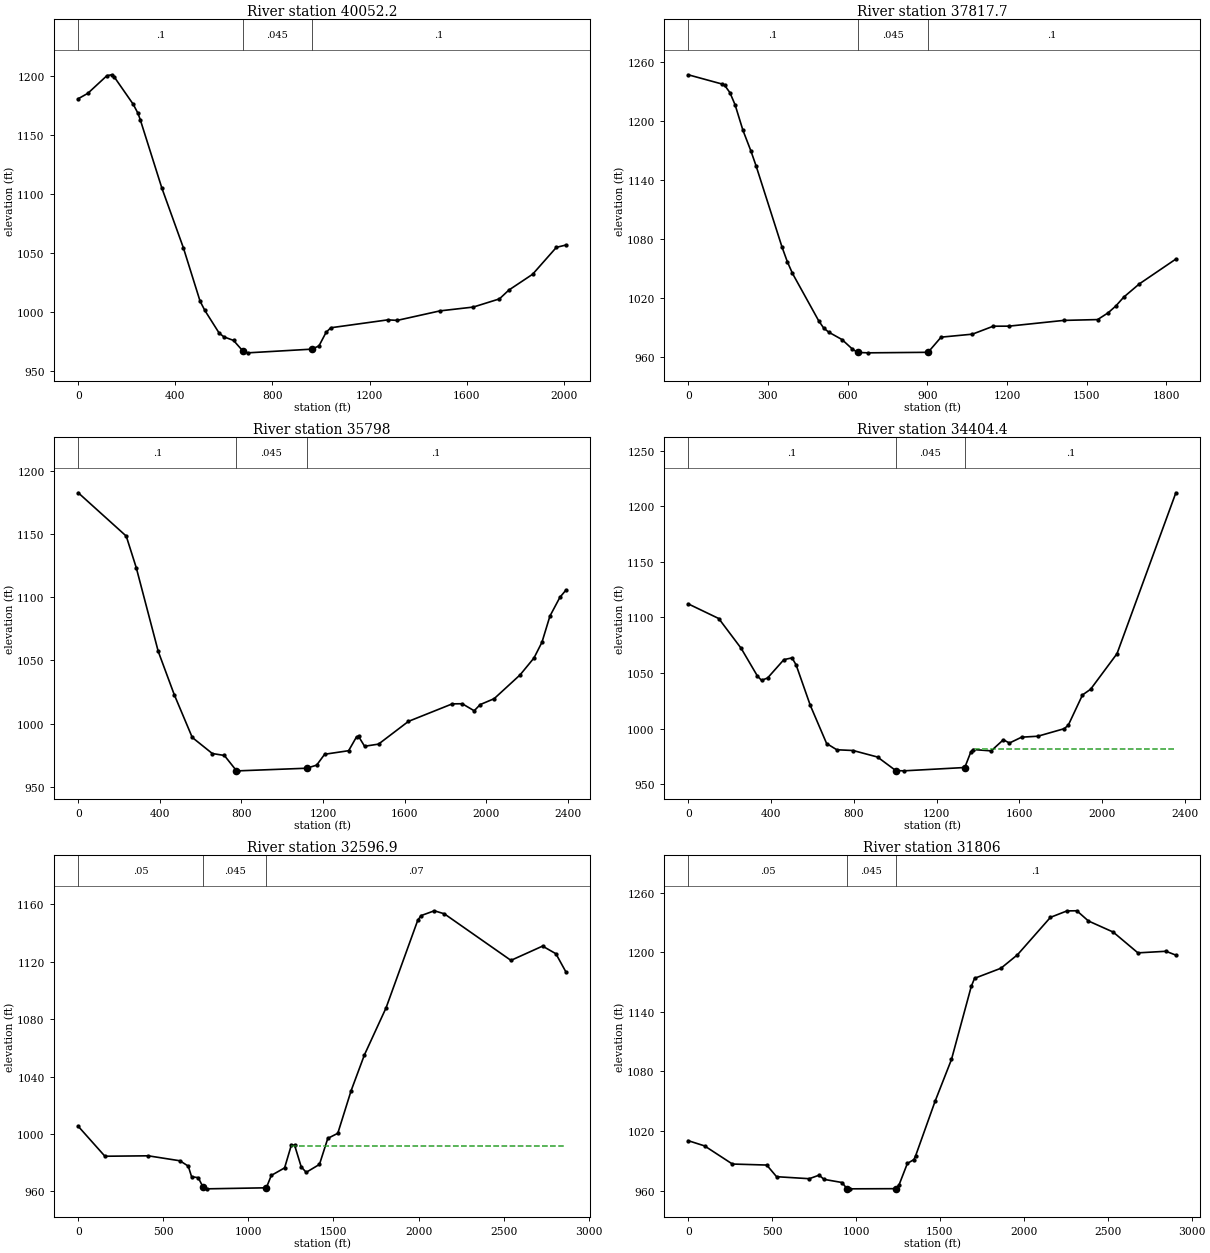
Type RM Length L Ch R = 1 ,40052.2 ,2257.5,2234.5,2211.5
XS GIS Cut Line= 4
     1808768.326      314854.602     1809434.993      314680.991
     1809872.714      314580.387     1810712.192      314349.393
#Sta/Elev= 30
       0 1180.81    39.4 1185.36   118.1 1200.34   137.8  1201.1   147.6 1199.48
   226.4 1176.12     246 1168.48   255.9 1162.77   344.4 1105.11     433  1054.5
   501.9 1009.18   521.6 1001.31   580.6   982.1   600.3  978.92   639.7  975.92
   679.1  966.73   698.7   965.4   962.3  968.53   991.6  971.27  1020.9  982.76
  1040.4  986.66    1275  993.35  1314.1  992.92  1490.2 1000.97  1627.2  1004.2
  1734.8 1011.11  1773.9 1018.62  1871.8 1032.03  1969.6 1054.83  2008.7 1056.77
#Mann= 3 , 0 , 0
       0      .1       0   679.1    .045       0   962.3      .1       0
Bank Sta=679.1,962.3
XS Rating Curve= 0 ,0
Exp/Cntr=0.3,0.1

Type RM Length L Ch R = 1 ,37817.7 ,2018.1,2019.7,2021.3
XS GIS Cut Line= 3
     1811106.091      316498.793     1811357.591      315755.209
     1811722.174      314769.966
#Sta/Elev= 30
       0 1247.35   127.6 1237.91   137.4 1236.52     157 1229.17   176.6 1216.65
     206 1190.79   235.5  1170.1   255.1 1154.86   353.2 1071.78   372.9 1057.05
   392.5    1045   490.6     997   510.2  989.24   529.8  985.03   578.9  977.62
   618.2  967.89   637.8  964.51     677   964.1   902.8  964.64   951.9  980.08
  1069.7  983.12  1148.2  991.23  1207.1  991.28  1413.3  997.14    1541  997.98
  1580.2 1004.79  1609.7 1011.85  1639.1 1020.79    1698 1034.33  1835.5 1059.62
#Mann= 3 , 0 , 0
       0      .1       0   637.8    .045       0   902.8      .1       0
Bank Sta=637.8,902.8
XS Rating Curve= 0 ,0
Exp/Cntr=0.3,0.1

Type RM Length L Ch R = 1 ,35798   ,1380.4,1393.6,1406.5
XS GIS Cut Line= 4
     1812977.931      316964.255      1813179.32      316485.088
     1813464.042      315804.532     1813984.875      314797.588
#Sta/Elev= 30
       0 1182.49   235.4 1148.26   284.4 1123.36   392.3 1057.16   470.7 1023.03
   559.1  989.18   657.5  976.48   716.5  974.95   775.5  962.98   785.3   962.8
  1119.8  964.86    1169   967.3  1208.3   975.9  1325.9  978.71    1365  989.76
  1374.8  989.96  1404.1  982.22  1472.5  983.91  1619.1 1001.87  1834.1 1015.72
    1883 1015.81  1941.6 1010.26  1970.9 1015.14  2039.3 1019.79  2166.4 1038.58
  2234.8 1051.98  2273.9 1064.42    2313 1085.09  2361.8 1099.88  2391.2 1105.54
#Mann= 3 , 0 , 0
       0      .1       0   775.5    .045       0  1119.8      .1       0
Bank Sta=775.5,1119.8
XS Rating Curve= 0 ,0
Exp/Cntr=0.3,0.1

Type RM Length L Ch R = 1 ,34404.4 ,1786.4,1807.5,1828.4
XS GIS Cut Line= 3
     1813634.646      317299.046     1814394.194      316789.064
      1815576.92      315964.411
#Sta/Elev= 30
       0 1112.26   147.6 1099.06   255.8 1072.25   334.5 1047.27   354.2 1043.42
   383.7 1045.53   462.4 1062.04   501.7 1063.64   521.4 1057.33   590.2 1020.77
   668.9   986.5   718.1  980.88   796.8  980.21   914.9  974.34  1003.2  962.12
  1042.4   961.9  1336.6   964.9  1366.1  979.01  1375.9  981.09  1464.2  979.89
    1523  989.88  1552.4  986.94  1611.3  992.22  1689.7  993.07  1817.2  999.86
  1836.9 1003.04  1905.5 1030.24  1944.8  1035.4  2072.3 1067.41  2356.7  1212.3
#Mann= 3 , 0 , 0
       0      .1       0  1003.2    .045       0  1336.6      .1       0
#XS Ineff= 2 , 0
                         1385.86          981.33
Permanent Ineff=
       F       F
Bank Sta=1003.2,1336.6
XS Rating Curve= 0 ,0
Exp/Cntr=0.3,0.1

Type RM Length L Ch R = 1 ,32596.9 ,777.6,790.9,804.6
XS GIS Cut Line= 4
     1814513.552      317950.088     1815153.743      318167.102
     1815869.889      318394.966     1817247.927      318807.293
#Sta/Elev= 30
       0 1005.35   156.8   984.5   411.5   984.8   597.6  981.34   646.6  977.62
   666.2  970.24   705.2  969.58   734.5  962.81     754   961.8  1105.4  962.52
  1134.7  971.15  1212.8   976.4  1251.8     992  1271.3  992.28  1310.4  977.14
  1339.7  973.29  1417.7  978.82  1466.6  996.94  1525.4 1000.48  1603.6 1030.12
  1681.9 1055.08  1809.1 1087.85    1995 1148.72  2014.6 1152.07  2092.9 1155.44
  2151.6 1153.32    2543  1120.9  2728.9 1130.84  2807.2 1125.53  2865.9  1112.9
#Mann= 3 , 0 , 0
       0     .05       0   734.5    .045       0  1105.4     .07       0
#XS Ineff= 2 , 0
                          1251.1          991.91
Permanent Ineff=
       F       F
Bank Sta=734.5,1105.4
XS Rating Curve= 0 ,0
Exp/Cntr=0.3,0.1

Type RM Length L Ch R = 1 ,31806   ,1716.3,1728.3,1740.3
XS GIS Cut Line= 4
     1814122.927      318243.057     1814849.923      318698.786
     1815283.951      319273.873     1816000.097      320391.494
#Sta/Elev= 30
       0 1010.28    97.5 1005.01   263.3  986.76     468  985.74   526.5  974.02
   721.5     972     780  975.57   809.3  971.34   916.4  968.17   945.7  962.04
   965.1   961.8  1237.8  961.97  1257.2  966.14  1305.9  987.34  1344.8  991.26
  1354.6  994.81  1471.4 1050.05  1568.8 1091.99  1686.7  1165.5  1706.3 1173.66
  1863.7 1183.82    1962 1197.35  2158.6 1235.03    2257 1241.51    2316 1241.64
  2384.8 1231.38  2532.3 1220.23  2679.8 1199.28  2846.9 1200.88  2905.9 1197.02
#Mann= 3 , 0 , 0
       0     .05       0   945.7    .045       0  1237.8      .1       0
Bank Sta=945.7,1237.8
XS Rating Curve= 0 ,0
Exp/Cntr=0.3,0.1

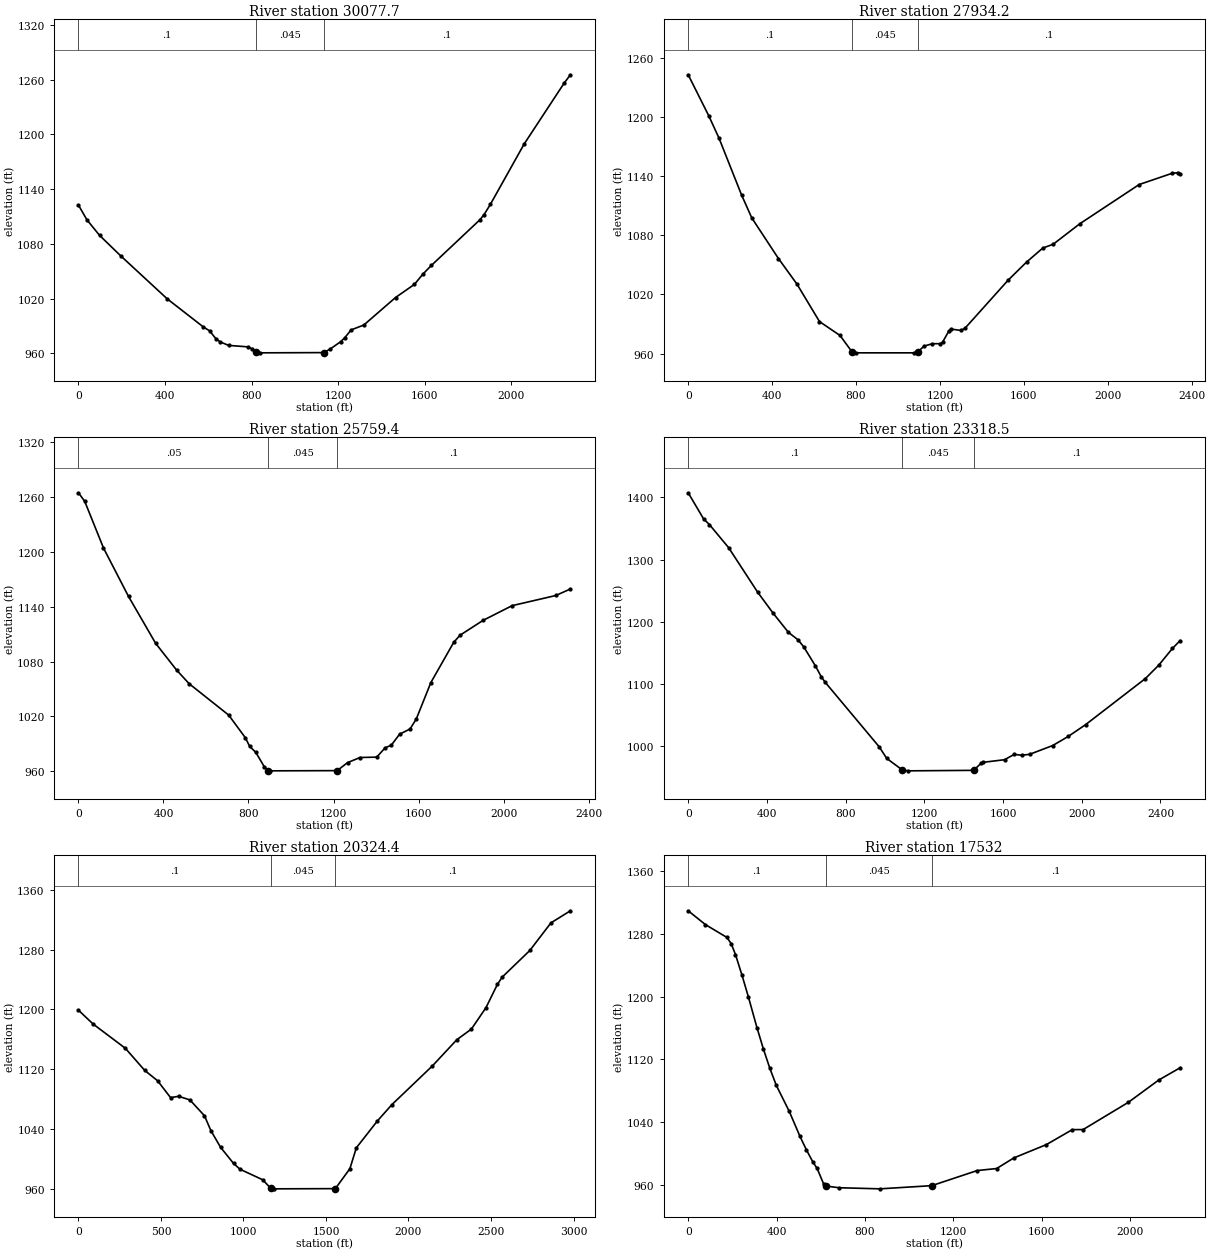
Type RM Length L Ch R = 1 ,30077.7 ,2164.8,2143.5,2126.6
XS GIS Cut Line= 4
     1813244.021      318579.428     1813428.482      319338.977
     1813504.437      319979.168     1813645.496      320814.671
#Sta/Elev= 30
       0 1122.58    39.1 1106.42    97.7 1089.35   195.4 1066.93   410.4 1019.81
   576.4  989.22   605.8  984.81   635.1  976.24   654.6  972.74   693.7  968.86
   781.6  967.28   801.2  965.26   820.7  961.49   840.2   960.7  1133.3  960.96
  1162.6  964.74  1211.4  972.85    1231  977.29  1260.2  985.83  1318.9  991.16
  1465.3 1021.28  1552.9 1035.74  1591.9 1046.95  1630.8 1056.38  1854.8 1106.34
  1874.3 1112.03  1903.5 1123.23  2059.4  1189.3  2244.4 1256.07  2273.6 1265.31
#Mann= 3 , 0 , 0
       0      .1       0   820.7    .045       0  1133.3      .1       0
Bank Sta=820.7,1133.3
XS Rating Curve= 0 ,0
Exp/Cntr=0.3,0.1

Type RM Length L Ch R = 1 ,27934.2 ,2171.7,2174.7,2178.6
XS GIS Cut Line= 4
     1810835.166      319631.945     1811421.104      320120.227
     1811887.684      320521.702     1812354.264      321368.057
#Sta/Elev= 30
       0 1242.65    97.8 1201.18   146.7 1178.49   254.2 1120.88   303.1 1097.51
   430.2 1056.33   518.3 1030.42   625.8  992.41   723.6  978.31   782.3  961.26
   801.8   960.7  1075.4   960.7  1094.9   961.8  1124.2  967.51  1163.3  969.94
  1202.4     970  1212.2   971.4  1241.5  982.51  1251.2  984.82  1300.1  983.42
  1319.6   985.7  1524.7 1034.35  1612.5  1052.7  1690.6 1067.03  1739.4 1070.77
  1866.4 1091.56  2149.4 1131.35  2305.6  1142.7  2334.9 1143.42  2344.7 1142.15
#Mann= 3 , 0 , 0
       0      .1       0   782.3    .045       0  1094.9      .1       0
Bank Sta=782.3,1094.9
XS Rating Curve= 0 ,0
Exp/Cntr=0.3,0.1

Type RM Length L Ch R = 1 ,25759.4 ,2431.4,2441,2449.7
XS GIS Cut Line= 3
     1809397.666      321041.234     1810123.118      321841.286
     1810911.555      322791.234
#Sta/Elev= 30
       0 1264.66    29.4 1255.37   117.8 1204.26   235.6 1151.24   363.3 1099.94
   461.4 1070.83   520.4 1055.89   706.9 1021.47   785.4  996.64   805.1  987.43
   834.5  980.66   873.8  965.16   893.4  960.79   903.3   960.5  1217.2  960.73
  1266.1  969.48  1324.9  975.09  1403.3  975.49  1442.5  985.63  1471.9  988.56
  1511.1 1000.64  1560.1 1006.27  1589.5 1017.27    1658 1057.06  1765.8 1101.14
  1795.2 1108.82    1903 1125.01  2040.2 1141.18  2245.9  1152.3  2314.5 1159.43
#Mann= 3 , 0 , 0
       0     .05       0   893.4    .045       0  1217.2      .1       0
Bank Sta=893.4,1217.2
XS Rating Curve= 0 ,0
Exp/Cntr=0.3,0.1

Type RM Length L Ch R = 1 ,23318.5 ,2980.7,2994,3007.4
XS GIS Cut Line= 3
     1807751.833      321902.345       1807918.5      322506.511
     1808487.944      324291.234
#Sta/Elev= 30
       0  1407.2    78.3 1365.22   107.7 1356.19   205.6 1318.98   352.5 1247.74
   430.9 1214.08   509.2 1183.01   558.2 1170.97   587.6 1159.52   646.4 1129.14
   675.8 1111.92   695.4 1103.08     970  999.37  1009.2   980.4  1087.7  962.04
  1117.1   960.5  1450.6  961.29  1489.9   973.1  1499.7  974.21  1607.6  978.37
  1656.6   986.9  1695.8  985.61  1735.1  987.02  1852.8 1001.19  1931.2 1015.72
  2019.5 1034.66  2323.6 1108.78  2392.2 1130.53  2460.9 1157.16  2500.1 1169.75
#Mann= 3 , 0 , 0
       0      .1       0  1087.7    .045       0  1450.6      .1       0
Bank Sta=1087.7,1450.6
XS Rating Curve= 0 ,0
Exp/Cntr=0.3,0.1

Type RM Length L Ch R = 1 ,20324.4 ,2812,2792.5,2772.9
XS GIS Cut Line= 4
     1805633.777      321471.789     1805369.889      322485.678
     1805126.833      323312.067     1804939.333      324367.623
#Sta/Elev= 30
       0  1198.8    88.1 1180.41     284 1147.85   401.4 1118.26   479.8 1104.31
   558.1 1081.78   607.1 1083.56   675.6 1078.68   763.7  1057.5   802.9 1037.43
   861.6 1015.18     940  993.67   979.1  985.91  1116.2  971.86  1165.1  960.57
  1184.7   959.7  1556.7  959.98  1644.8  986.66  1683.9 1014.59  1811.2  1050.5
  1899.3 1072.39  2145.1 1124.29  2292.6 1159.23  2381.2 1173.54  2469.7 1202.27
  2538.5 1233.24    2568 1243.12  2735.2  1278.7  2863.1 1315.64  2981.1 1331.85
#Mann= 3 , 0 , 0
       0      .1       0  1165.1    .045       0  1556.7      .1       0
Bank Sta=1165.1,1556.7
XS Rating Curve= 0 ,0
Exp/Cntr=0.3,0.1

Type RM Length L Ch R = 1 ,17532   ,2991.6,2980.9,2968.9
XS GIS Cut Line= 4
     1802085.166      322631.511     1802425.444      323117.623
     1803089.946      324133.085     1803336.589      324472.378
#Sta/Elev= 30
       0 1309.26    77.8  1291.7   175.1 1275.34   194.6 1267.39     214 1253.52
   243.2 1227.49   272.4  1199.6   311.3 1160.34   340.5 1133.08   369.6 1108.56
   398.8 1086.89   457.2 1053.89   505.8 1021.99     535 1004.77   564.2  989.35
   583.6  981.02     613  961.29   622.7  958.73   681.5  956.53   867.4  955.11
  1102.3  959.16  1307.8  978.38  1395.9  980.98  1474.2  994.55    1621 1011.45
  1738.4  1030.5  1787.4 1030.61  1992.3 1065.34  2128.8 1093.55  2226.4 1109.34
#Mann= 3 , 0 , 0
       0      .1       0   622.7    .045       0  1102.3      .1       0
Bank Sta=622.7,1102.3
XS Rating Curve= 0 ,0
Exp/Cntr=0.3,0.1

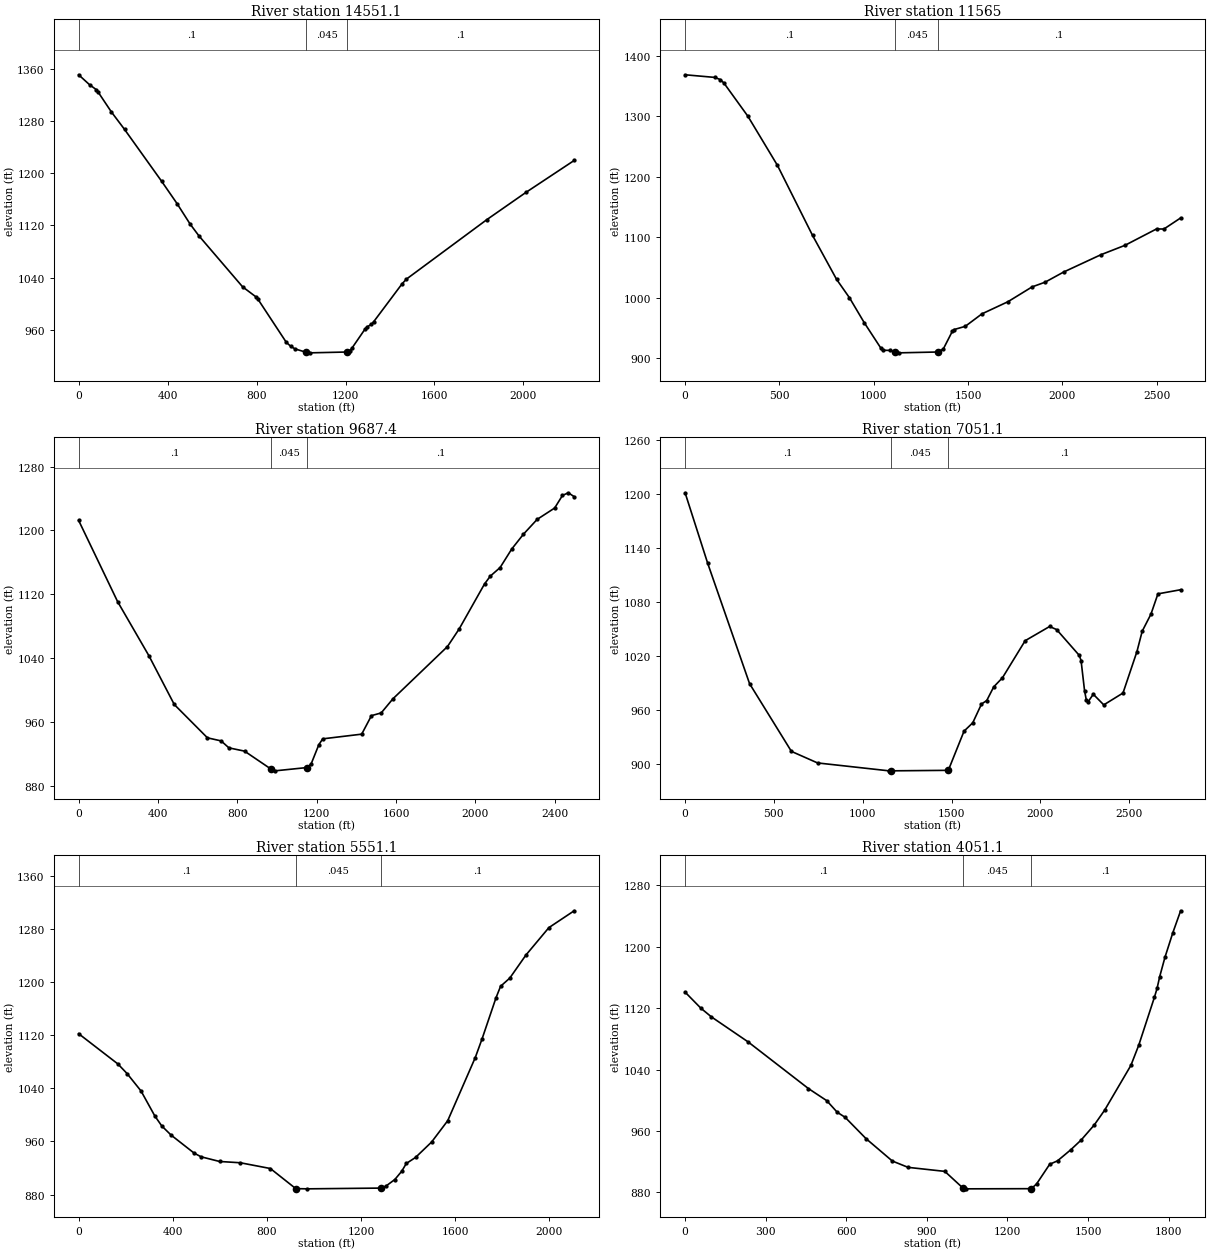
Type RM Length L Ch R = 1 ,14551.1 ,2983.9,2986.1,2989.5
XS GIS Cut Line= 3
     1800342.111        325457.9     1801317.002      326010.174
     1802307.389      326506.511
#Sta/Elev= 30
       0  1350.6    49.1 1335.38    78.6 1328.02    88.5 1323.69   147.4 1293.62
   206.4 1266.95   373.5 1187.34   442.3 1153.41   501.3 1121.94   540.6 1104.01
   737.1 1025.86   796.1 1010.73   805.9 1007.03   933.7  940.82   953.4  934.73
     973   930.7  1022.2  925.63  1041.8  924.68  1208.7  925.96  1218.5  927.86
  1228.3  931.54  1287.1  960.75  1296.9  964.37  1316.5  968.38  1326.3  972.15
  1453.8 1030.15  1473.4 1037.48  1836.1 1128.85  2012.6 1170.73  2228.2 1219.36
#Mann= 3 , 0 , 0
       0      .1       0  1022.2    .045       0  1208.7      .1       0
Bank Sta=1022.2,1208.7
XS Rating Curve= 0 ,0
Exp/Cntr=0.3,0.1

Type RM Length L Ch R = 1 ,11565   ,1864.9,1877.5,1889.9
XS GIS Cut Line= 4
     1798949.341      327956.211      1799719.74      328477.045
     1800164.619      328791.715     1801293.091      329019.579
#Sta/Elev= 30
       0  1368.9   156.6 1364.57     186 1361.04   205.6 1355.28   332.8 1300.24
   489.4 1218.91   675.4    1103   802.7 1030.28   871.2  999.72   949.4  958.51
    1037  916.58  1046.7  912.84  1085.6  912.68  1114.8  909.43  1134.3   908.6
  1338.6  909.98  1367.8  914.63  1416.5  944.41  1426.2  947.22  1484.7  952.46
  1573.2  973.14    1711  993.24  1838.9 1017.76  1907.8 1025.56  2006.2 1042.38
    2203 1070.93  2330.9 1086.55  2498.2 1113.68  2537.5 1113.57  2626.1 1131.91
#Mann= 3 , 0 , 0
       0      .1       0  1114.8    .045       0  1338.6      .1       0
Bank Sta=1114.8,1338.6
XS Rating Curve= 0 ,0
Exp/Cntr=0.3,0.1

Type RM Length L Ch R = 1 ,9687.4  ,2647.5,2636.3,2626.2
XS GIS Cut Line= 4
     1798102.987      328943.624     1798528.877      329674.527
     1798671.487      330010.091     1799288.425      331139.371
#Sta/Elev= 30
       0 1212.46   196.7  1110.6   354.1 1042.97     482  981.85   649.2  940.09
   718.1  936.24   757.4  927.53   836.1  923.43   970.7  900.74   989.9  898.74
    1153  902.91  1172.2  907.66  1210.5  931.45  1230.2  938.82  1426.6   944.7
  1475.8  967.89  1524.9   971.3  1583.8  988.94  1858.9 1054.46  1917.8  1076.5
  2045.5 1132.81    2075 1142.75  2124.1  1153.4    2183 1176.73    2242 1195.26
  2310.7 1213.73  2399.1    1228  2438.4 1243.76  2467.9 1247.09  2497.4 1242.22
#Mann= 3 , 0 , 0
       0      .1       0   970.7    .045       0    1153      .1       0
Bank Sta=970.7,1153
XS Rating Curve= 0 ,0
Exp/Cntr=0.3,0.1

Type RM Length L Ch R = 1 ,7051.1  ,1478.9,1500,1520.1
XS GIS Cut Line= 3
     1796388.577      330777.392     1797454.085      331628.005
     1798526.164      332567.756
#Sta/Elev= 30
       0 1201.73   127.5 1123.16   362.9  989.57   598.3  914.33   745.4  901.49
  1147.6   892.7  1157.4   892.7  1481.4  893.26  1569.9  936.79    1619  946.11
  1668.2  966.94  1697.7  970.84    1737  986.02  1786.2  996.15    1914 1037.34
  2051.6 1053.12    2091  1049.7  2218.8 1020.94  2228.6 1015.25  2248.3  981.64
  2258.1  971.51    2268   969.4  2297.4  977.81  2356.4     966  2464.6  979.19
  2543.2 1025.33  2572.7 1047.89  2621.9 1066.85  2661.2 1089.39    2789 1093.98
#Mann= 3 , 0 , 0
       0      .1       0  1157.4    .045       0  1481.4      .1       0
Bank Sta=1157.4,1481.4
XS Rating Curve= 0 ,0
Exp/Cntr=0.3,0.1

Type RM Length L Ch R = 1 ,5551.1  ,1478,1500,1521.4
XS GIS Cut Line= 3
     1796139.011       331059.51     1796099.586      332138.847
     1796063.056      333164.545
#Sta/Elev= 30
       0  1122.6   166.9 1076.94   206.2 1062.36   265.1 1036.26     324  998.43
   353.5  983.41   392.8  969.73   490.9  942.48   520.4  936.93   598.9  929.87
   687.3  927.92     815  919.24     923  888.91     972  888.59  1285.3  889.73
  1304.9   892.4    1344  902.63  1373.3  915.07  1392.8  926.83    1432  935.92
  1500.4   959.2  1568.8  991.33  1686.1 1086.67  1715.4  1115.3  1774.1 1176.71
  1793.6 1194.11  1832.7 1206.44  1901.1  1241.1  1998.9 1282.57  2106.4 1307.98
#Mann= 3 , 0 , 0
       0      .1       0     923    .045       0  1285.3      .1       0
Bank Sta=923,1285.3
XS Rating Curve= 0 ,0
Exp/Cntr=0.3,0.1

Type RM Length L Ch R = 1 ,4051.1  ,1636,1633.4,1631.4
XS GIS Cut Line= 3
     1795943.699      330668.885     1794960.067      331287.544
     1794392.064      331665.969
#Sta/Elev= 30
       0 1140.88    58.6 1119.98    97.6 1108.71   234.4 1076.07     459 1015.27
   527.3  999.46   566.4  984.33   595.6  977.82   673.8  949.89   771.4  920.82
     830  912.59   966.7  907.35  1035.1  885.33  1044.8   884.6  1288.8  884.81
  1308.3  891.02    1357  916.57  1386.3  921.11    1435  935.34    1474  948.12
  1522.8  967.72  1561.8   987.2  1659.3  1045.4  1688.5 1071.65    1747 1134.28
  1756.8 1145.76  1766.5 1161.01    1786 1186.13  1815.3 1218.13  1844.5 1246.86
#Mann= 3 , 0 , 0
       0      .1       0  1035.1    .045       0  1288.8      .1       0
Bank Sta=1035.1,1288.8
XS Rating Curve= 0 ,0
Exp/Cntr=0.3,0.1

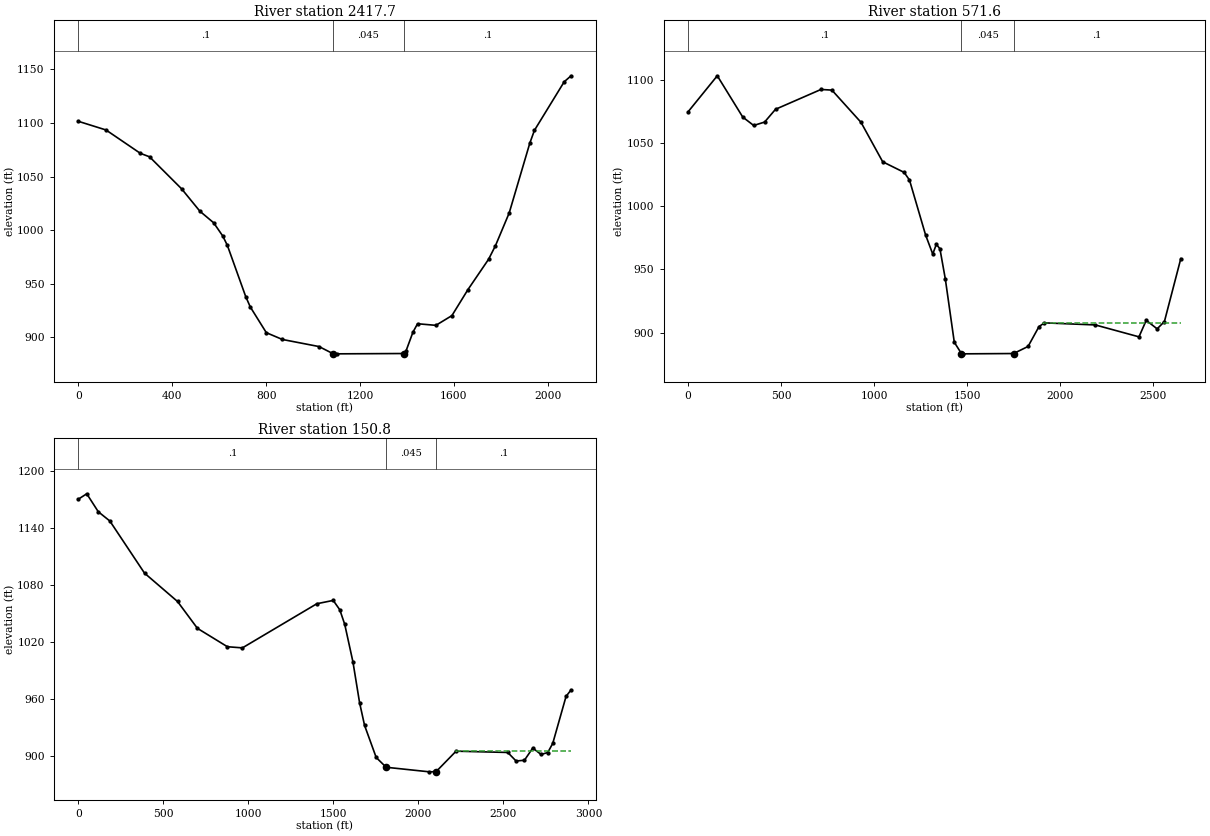
Type RM Length L Ch R = 1 ,2417.7  ,1861.5,1846.1,1830.7
XS GIS Cut Line= 3
     1795368.612      329171.489     1794348.647      329768.277
     1793632.501      330343.364
#Sta/Elev= 30
       0  1101.5   117.2 1093.47   263.7 1071.67   302.8 1068.44   439.5 1038.59
   517.6 1017.66   576.2 1006.89   615.3  994.47   634.8  985.74   712.9  938.06
   732.5  928.32   800.8  904.35   869.2  898.01  1025.5  891.39  1084.1  884.88
  1103.6   884.6  1386.9   884.9  1396.7  887.45    1426  904.84  1445.6  912.68
  1523.7  911.19  1592.1  920.28  1660.5  944.56  1748.4  972.82  1777.8  985.53
  1836.4  1016.1  1924.3 1081.25  1943.9 1093.12  2070.9 1138.45  2100.2 1144.02
#Mann= 3 , 0 , 0
       0      .1       0  1084.1    .045       0  1386.9      .1       0
Bank Sta=1084.1,1386.9
XS Rating Curve= 0 ,0
Exp/Cntr=0.3,0.1

Type RM Length L Ch R = 1 ,571.6   ,436.4,420.7,404.8
XS GIS Cut Line= 5
     1794122.627      328058.642     1793211.119      328464.101
      1792924.71      328600.308     1792851.793      329048.225
     1793039.293        329907.6
#Sta/Elev= 30
       0 1074.68   156.5 1103.06   293.4 1070.42   352.1 1063.79   410.8 1066.47
   469.5 1076.57     714 1092.25   772.7 1091.73   929.2 1066.24  1045.7 1035.09
    1161  1026.7  1189.8 1020.64  1276.3  977.23  1314.8  962.16  1334.1  969.86
  1353.4   966.3  1382.4  942.46  1430.6  892.47  1469.3  883.43  1478.9   883.3
  1749.3  883.54  1827.2  889.13  1885.9  904.82  1915.2  907.79  2188.8  906.14
  2423.4  896.73  2462.5  909.78  2521.1  903.05  2560.2  908.82  2648.2  958.51
#Mann= 3 , 0 , 0
       0      .1       0  1469.3    .045       0  1749.3      .1       0
#XS Ineff= 2 , 0
                         1905.78           907.5
Permanent Ineff=
       F       F
Bank Sta=1469.3,1749.3
XS Rating Curve= 0 ,0
Exp/Cntr=0.3,0.1

Type RM Length L Ch R = 1 ,150.8   ,155.9,150.8,146.1
XS GIS Cut Line= 6
     1792941.203      327327.305     1792560.995      327806.472
     1792430.786      328389.805     1792373.495      328790.847
     1792602.661      329223.138      1792951.62       329936.68
#Sta/Elev= 30
       0 1170.88    48.6 1176.47   116.5 1157.52   184.5 1147.76   388.4 1092.82
   582.6 1062.92   699.9 1034.57   876.2  1015.2   964.4    1014  1402.3 1060.54
  1498.7 1064.04  1537.3 1054.15  1566.3 1038.86  1614.5  999.38  1653.6  956.33
    1683   932.3  1751.5  898.43  1810.2  888.12  2064.6   883.3  2103.8   883.5
  2221.4  905.09  2525.4  903.74  2574.5  894.72  2623.5  895.51  2672.5  908.37
  2721.6  901.59  2760.8  903.68  2790.2   913.3  2868.6  962.92  2898.1  969.71
#Mann= 3 , 0 , 0
       0      .1       0  1810.2    .045       0  2103.8      .1       0
#XS Ineff= 2 , 0
                         2218.41          905.19
Permanent Ineff=
       F       F
Bank Sta=1810.2,2103.8
XS Rating Curve= 0 ,0
Exp/Cntr=0.3,0.1

Chan Stop Cuts=-1
Use User Specified Reach Order=0
Composite Channel Slope=5